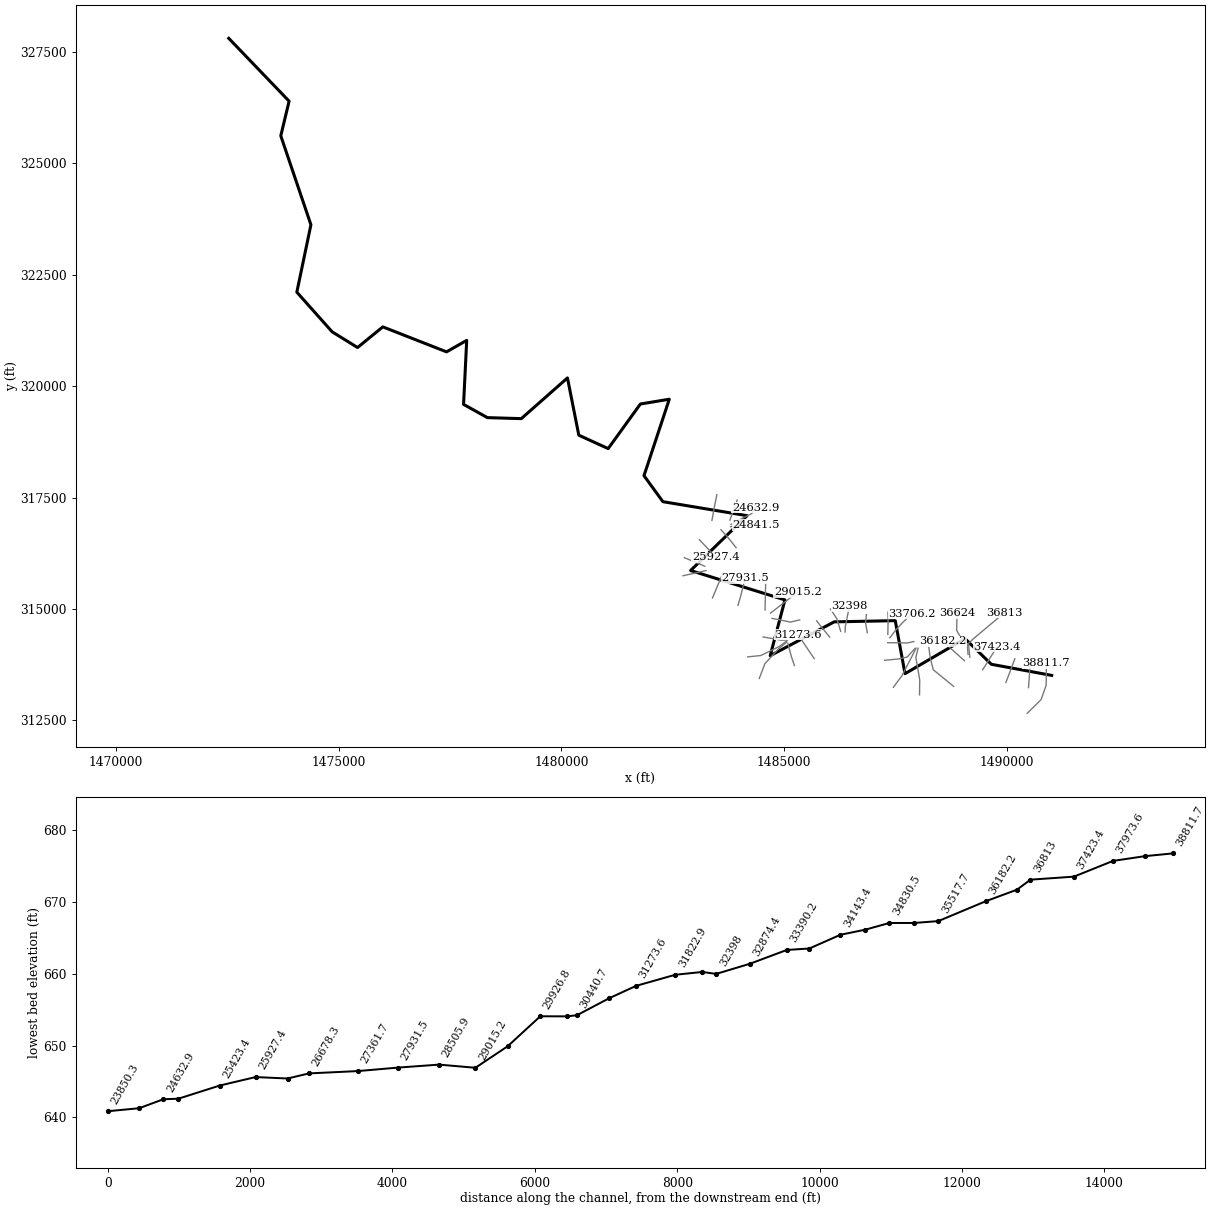
--- FrenchCr.prj (project) ---

Proj Title=FrenchCr
Current Plan=p01
Default Exp/Contr=0,0
English Units
Geom File=g01
Flow File=f01
Plan File=p01
BEGIN DESCRIPTION:
AMEC Environment & Infrastructure, 2013
Projection: NAD 1983 State Plane West Virginia North FIPS 4701 (US Feet)
Vertical Datum: NAVD 1988
END DESCRIPTION:
DSS Export Rating Curves= 0
DSS Export Rating Curve Sorted= 0
DSS Export Volume Flow Curves= 0
DXF OffsetX= 0
DXF OffsetY= 0
DXF ScaleX= 0
DXF ScaleY= 0

--- FrenchCr.p01 (plan) ---

Plan Title=Floodplain
Program Version=4.00
Geom File=g01
Flow File=f01
K Sum by GR=0
Std Step Tol=0.01
Critical Tol=0.01
Num of Std Step Trials=20
Max Error Tol=0.3
Flow Tol Ratio=0.001
Split Flow NTrial=30
Split Flow Tol=0.02
Split Flow Ratio=0.02
Log Output Level=0
Friction Slope Method=1
Unsteady Friction Slope Method=2
Unsteady Bridges Friction Slope Method=1
Global Log Level=0
CheckData=False
Run HTab=0
Run UNet=0
Run PostProcess=0
UNET Theta=0
UNET Theta Warmup=0
UNET ZTol=0
UNET ZSATol=0
UNET MxIter=0
UNET MaxInSteps=0
UNET DtIC=0
UNET DtMin=0
UNET MaxCRTS=0
UNET WFStab=0
UNET SFStab=0
UNET WFX=0
UNET SFX=0
UNET DSS MLevel=0
UNET DZMax Abort=0
UNET Convert EG Bridges=0
UNET Use Existing IB Tables=0
UNET Froude Limit=0
UNET Froude Power=0
Write IC File=0
Echo Input=False
Echo Output=False
Write Detailed=0

--- FrenchCr.f01 (steady flow) ---

Flow Title=USGS Regress. Eqn. (2010) - Western-Plateaus
Program Version=4.10
Number of Profiles= 1
Profile Names=P100yr
River Rch & RM=FrenchCr,Main            ,38811.7
    3278
River Rch & RM=FrenchCr,Main            ,35517.7
    3377
River Rch & RM=FrenchCr,Main            ,34830.5
    3681
River Rch & RM=FrenchCr,Main            ,30440.7
    3774
River Rch & RM=FrenchCr,Main            ,29468.2
    3891
River Rch & RM=FrenchCr,Main            ,20869.3
    4055
River Rch & RM=FrenchCr,Main            ,20299.9
    4477
Boundary for River Rch & Prof#=FrenchCr,Main            , 1
Up Type= 0
Dn Type= 3
Dn Slope=0.00217
DSS Import GetInterval= 0
DSS Import GetPeak= 0
DSS Import FillOption= 0

--- FrenchCr.g01 (geometry) ---

Geom Title=USGS 3m DEM
Program Version=4.10

River Reach=FrenchCr        ,Main
Reach XY= 30
     1491003.616      313511.582      1489648.33      313760.834
     1489058.391      314335.324     1487710.977      313550.034
      1487492.08      314740.001     1486121.585      314713.101
     1484684.789      313953.542     1485015.943      315205.538
     1482897.887      315865.261     1484165.183      317096.077
     1482276.294      317410.096     1481851.815      317993.429
     1482420.276      319709.149     1481770.494      319601.679
     1481047.838      318601.245     1480389.201      318901.809
     1480134.176      320187.448     1479097.751      319273.554
     1478337.084      319296.346     1477802.178       319593.65
     1477872.708      321030.282     1477420.234      320772.035
     1475990.112      321333.016     1475422.621      320869.691
      1474852.96      321221.254      1474059.74      322112.057
     1474376.146      323623.993     1473699.748      325620.993
      1473886.38      326397.903      1472532.18      327808.224

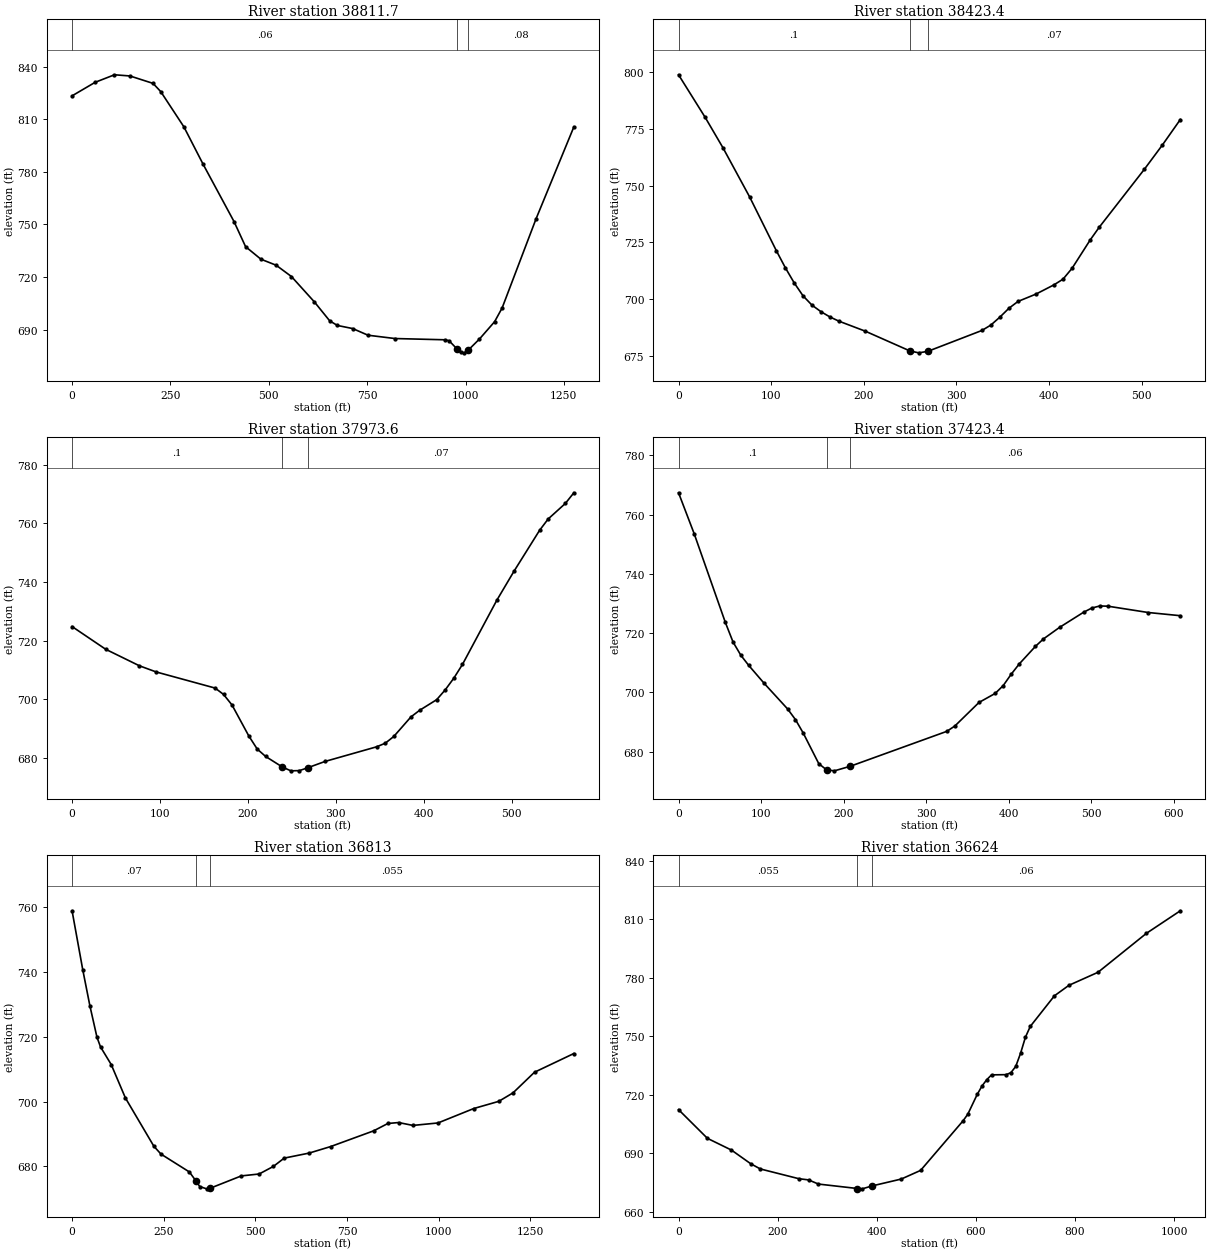
Type RM Length L Ch R = 1 ,38811.7 ,389.3,388.4,386.4
XS GIS Cut Line= 5
     1490452.026      312659.233     1490765.828      312969.129
     1490878.645      313290.176     1490882.508      313477.092
     1490883.883      313784.233
#Sta/Elev= 30
       0  823.32    58.8  831.06   107.8  835.34     147  834.67   205.8  830.43
   225.4  825.74   284.2  805.64   333.2  784.25   411.6  751.62     441  737.29
   479.9  730.14   518.8  726.68   557.7  720.22     616  705.74   654.9  694.94
   674.4  692.33   713.3  690.56   752.2  686.76   820.7  684.87   948.6  684.15
   958.4  683.57   977.9  679.05   987.5  676.92   997.1  676.71  1006.7   678.2
  1035.5   684.6  1073.9  694.46  1093.1  702.32  1179.4  753.22  1275.4  805.61
#Mann= 3 , 0 , 0
       0     .06       0   977.9    .045       0  1006.7     .08       0
Bank Sta=977.9,1006.7
XS Rating Curve= 0 ,0
Exp/Cntr=0.3,0.1

Type RM Length L Ch R = 1 ,38423.4 ,456.2,449.8,443
XS GIS Cut Line= 3
     1490482.408      313236.838     1490501.408      313495.386
       1490519.3      313777.202
#Sta/Elev= 30
       0  798.86    28.8  780.06      48  766.66    76.8  744.99   105.6  721.31
   115.2  713.89   124.8  707.18   134.4  701.44     144  697.36   153.6   694.5
   163.2  692.19   172.8  690.34   201.6  685.87   249.6  677.19   259.2  676.33
     269  676.98   327.4  686.18   337.1  688.57   346.9  692.09   356.6  695.97
   366.4  698.98   385.8  702.22   405.3  706.31     415   708.8   424.8  713.61
   444.3  726.06     454  731.64   502.7  757.17   522.2  767.89   541.6  779.14
#Mann= 3 , 0 , 0
       0      .1       0   249.6    .045       0     269     .07       0
Bank Sta=249.6,269
XS Rating Curve= 0 ,0
Exp/Cntr=0.3,0.1

Type RM Length L Ch R = 1 ,37973.6 ,554.8,550.2,545.8
XS GIS Cut Line= 3
     1489974.595      313351.855     1490063.976      313584.148
     1490176.418      313885.709
#Sta/Elev= 30
       0  724.83    38.3  717.08    76.6  711.46    95.7  709.36   162.7  703.87
   172.3   701.7   181.9  698.11     201  687.56   210.6  683.08   220.2  680.56
   239.3  676.95   248.9  675.67   258.6  675.75   268.4  676.76   287.9  678.89
   346.4  683.86   356.2  685.08   365.9  687.38   385.4  694.04   395.2  696.28
   414.7  699.92   424.4  703.26   434.2  707.25     444  711.92     483  733.75
   502.5  743.62   531.7  757.61   541.5  761.49     561  766.77   570.7  770.41
#Mann= 3 , 0 , 0
       0      .1       0   239.3    .045       0   268.4     .07       0
Bank Sta=239.3,268.4
XS Rating Curve= 0 ,0
Exp/Cntr=0.3,0.1

Type RM Length L Ch R = 1 ,37423.4 ,615.7,610.3,604.5
XS GIS Cut Line= 3
     1489453.762      313638.313     1489560.841      313805.271
     1489775.215      314154.588
#Sta/Elev= 30
       0  767.38    18.9   753.6    56.7  723.63    66.1  716.96    75.6  712.48
      85  709.11   103.9  702.99   132.2  694.38   141.7  690.79   151.1  686.26
     170   675.9   179.5   673.8   188.9  673.48   208.1  675.02   325.2  686.82
     335  688.64   364.2  696.58   383.8  699.62   393.5  702.26   403.3  706.14
     413  709.59   432.6  715.52   442.3  718.03   461.8  721.92   491.1  727.06
   500.8  728.44   510.6  729.16   520.4  729.08   569.2  726.95   608.2  725.87
#Mann= 3 , 0 , 0
       0      .1       0   179.5    .045       0   208.1     .06       0
Bank Sta=179.5,208.1
XS Rating Curve= 0 ,0
Exp/Cntr=0.3,0.1

Type RM Length L Ch R = 1 ,36813   ,153.8,189,224.2
XS GIS Cut Line= 4
     1489165.133      313920.431     1489135.619      314229.459
     1489244.994      314333.626     1489939.873      314916.525
#Sta/Elev= 30
       0  758.87    29.1   740.7    48.5   729.6    67.9  719.85    77.6  716.86
   106.7  711.43   145.5   701.1   223.1   686.2   242.5  683.78   319.9  678.27
   338.8  675.36   348.2  673.77   367.1  673.06   376.5  673.24   461.5  677.05
   510.2  677.64   549.2  679.99   578.5  682.54   646.8   684.1   705.3  686.11
   822.3  690.95   861.3  693.23   890.6  693.52   929.6  692.63   997.9  693.39
  1095.4  697.84  1163.7  700.06  1202.7  702.69  1261.2  709.05  1368.5  714.82
#Mann= 3 , 0 , 0
       0     .07       0   338.8    .045       0   376.5    .055       0
Bank Sta=338.8,376.5
XS Rating Curve= 0 ,0
Exp/Cntr=0.3,0.1

Type RM Length L Ch R = 1 ,36624   ,439.3,441.8,444
XS GIS Cut Line= 5
     1489126.071      313983.365      1489106.54       314215.57
     1488941.609      314397.862     1488869.994       314521.56
     1488878.675      314912.185
#Sta/Elev= 30
       0  712.29    58.3  697.56   106.8  691.54   145.6  684.55   165.1  681.86
   242.9  676.86   262.5  676.25   282.2  674.12   360.9  671.84   370.7  671.67
   390.4  673.16   449.4  676.69   488.4  681.12   574.1  706.54   583.7  709.95
   602.7   720.1   612.3  724.39   621.8   727.6   631.6  730.11   660.9  730.21
   670.6  731.22   680.4  734.43   690.2  741.21   699.9  749.38   709.7  754.94
   758.5  770.65   787.8  776.04   846.4   782.7   944.1  802.68  1012.5  814.24
#Mann= 3 , 0 , 0
       0    .055       0   360.9    .045       0   390.4     .06       0
Bank Sta=360.9,390.4
XS Rating Curve= 0 ,0
Exp/Cntr=0.3,0.1

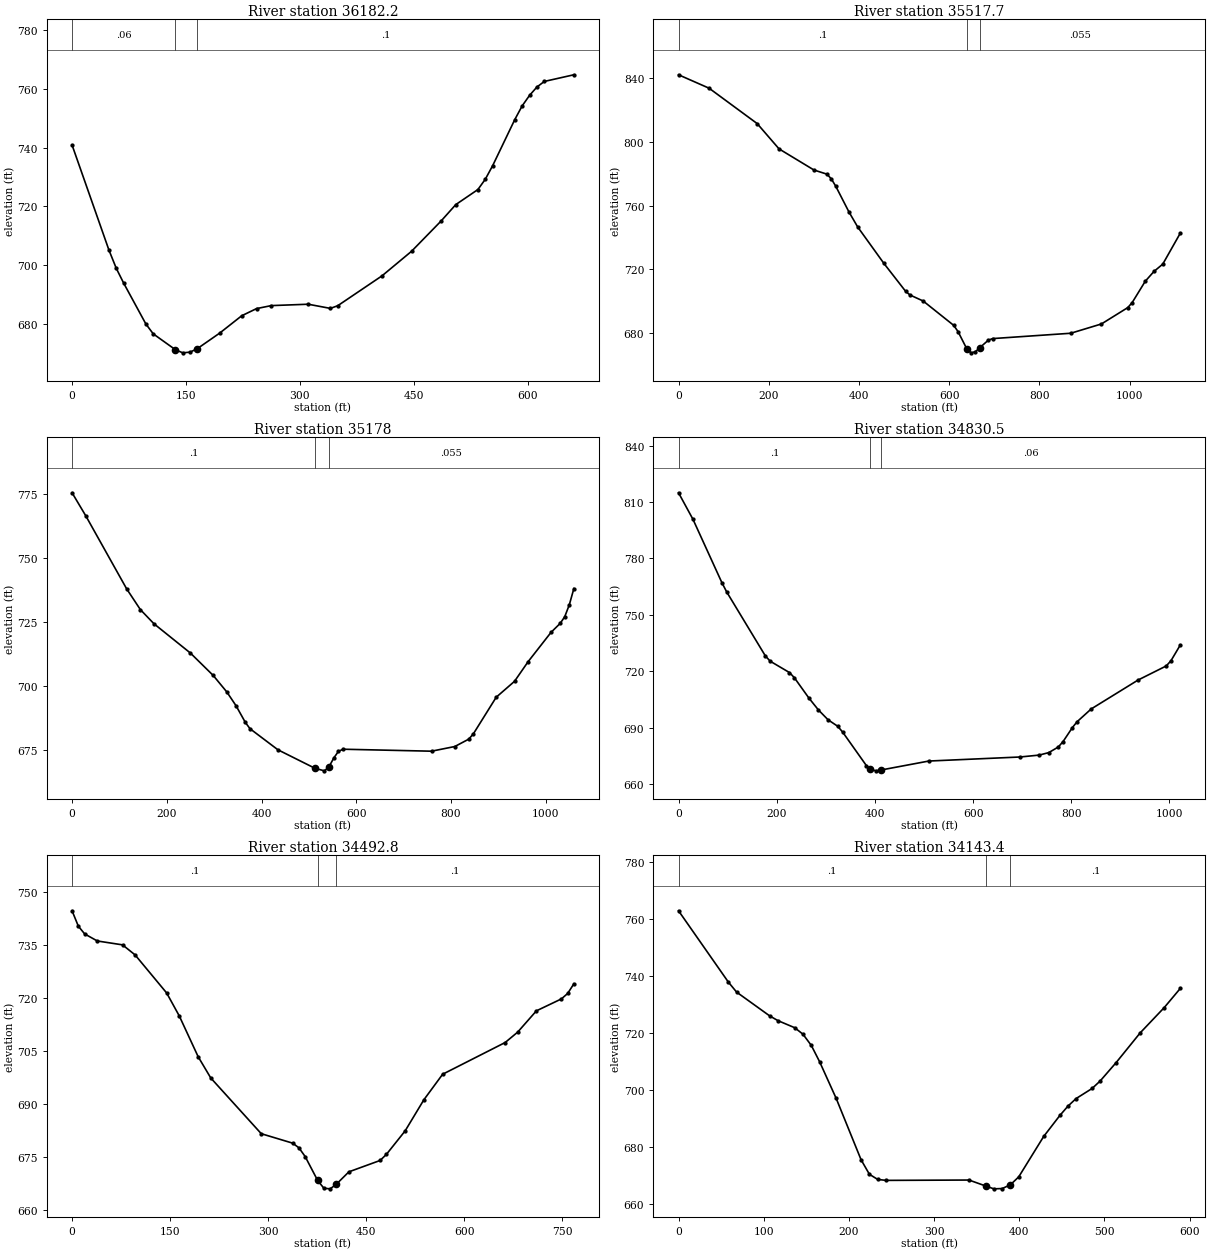
Type RM Length L Ch R = 1 ,36182.2 ,677.4,664.5,650.6
XS GIS Cut Line= 2
     1489045.776      313840.136     1488553.154      314280.674
#Sta/Elev= 30
       0  740.88    48.6  705.05    58.3  698.81      68  693.79    97.2  679.89
   106.9  676.52   136.1  671.12   145.8  670.05   155.5  670.29   165.2  671.52
   194.4  676.77   223.5   682.7     243  685.13   262.4  686.15     311  686.62
   340.2   685.2   349.9  686.11   408.2  696.29   447.1  704.66   485.9  714.95
   505.4  720.58   534.5  725.71   544.2   729.2     554  733.87   583.1  749.56
   592.8  754.22   602.6  757.83   612.3  760.67     622  762.56   660.9  764.83
#Mann= 3 , 0 , 0
       0     .06       0   136.1    .045       0   165.2      .1       0
Bank Sta=136.1,165.2
XS Rating Curve= 0 ,0
Exp/Cntr=0.3,0.1

Type RM Length L Ch R = 1 ,35517.7 ,341.2,339.7,337.2
XS GIS Cut Line= 4
      1488802.72      313265.049     1488344.821      313638.313
     1488277.142      313898.677     1488244.692      314149.219
#Sta/Elev= 30
       0  842.32    67.8  833.86   174.3  811.61   222.8  795.68   300.2  782.38
   329.3  779.74     339  776.67   348.6  772.13   377.7  756.03   397.1  746.55
   455.2  723.62   503.6  705.96   513.3  703.68   542.3  699.93     610   684.6
   619.6  680.69   638.8  669.94   648.4   667.3     658  667.98   667.6   670.5
   686.8  675.27   696.4  676.27   869.5  679.63   937.5  685.48   995.8  695.76
  1005.5  698.86  1034.7  712.37  1054.1  718.57  1073.5  723.15  1112.4  742.66
#Mann= 3 , 0 , 0
       0      .1       0   638.8    .045       0   667.6    .055       0
Bank Sta=638.8,667.6
XS Rating Curve= 0 ,0
Exp/Cntr=0.3,0.1

Type RM Length L Ch R = 1 ,35178   ,361.9,347.5,333.1
XS GIS Cut Line= 4
     1488036.661      313074.077     1488041.001      313410.449
     1487954.196      313913.921     1488004.109      314120.084
#Sta/Elev= 30
       0  775.46    28.8  766.52   115.3  737.98   144.2  729.91     173  724.37
   249.9  712.96     298  704.23   326.8  697.78   346.2  692.42   365.9   685.9
   375.7  683.46   434.6  675.25   513.2     668   532.9  667.04   542.7  668.71
   552.6  672.06   562.4  674.64   572.2  675.47   758.9   674.7     808  676.52
   837.5   679.4   847.3  681.48   895.5  695.75   934.1  701.94     963  709.65
  1011.2  721.03  1030.5  724.53  1040.1  727.12  1049.8  731.78  1059.4  738.11
#Mann= 3 , 0 , 0
       0      .1       0   513.2    .045       0   542.7    .055       0
Bank Sta=513.2,542.7
XS Rating Curve= 0 ,0
Exp/Cntr=0.3,0.1

Type RM Length L Ch R = 1 ,34830.5 ,357.1,337.7,317.3
XS GIS Cut Line= 4
     1487448.553      313243.348     1487641.696      313503.765
     1487847.859       313903.07     1487960.706      314124.424
#Sta/Elev= 30
       0  814.91    29.5  800.75    88.4  767.06    98.2  762.13   176.8  728.18
   186.7  725.34     226   719.3   235.8  716.61   265.3  705.83   284.9  699.43
   304.6  694.18   324.2  690.75     334  687.75   382.8  669.77   390.7  667.87
   402.4  667.04   412.2  667.47   509.8  672.25   695.5   674.4   734.5  675.41
   754.1  676.73   773.6  679.73   783.2  682.59   802.3  690.06   811.8  693.15
   840.5  699.94   936.1  715.34   993.4  722.82    1003  725.57  1022.1  733.99
#Mann= 3 , 0 , 0
       0      .1       0   390.7    .045       0   412.2     .06       0
Bank Sta=390.7,412.2
XS Rating Curve= 0 ,0
Exp/Cntr=0.3,0.1

Type RM Length L Ch R = 1 ,34492.8 ,354.8,349.5,344
XS GIS Cut Line= 4
     1487255.411      313850.987     1487572.251      313881.369
     1487758.883      313922.601     1487932.494      314113.574
#Sta/Elev= 30
       0  744.75     9.6  740.39    19.3   738.2    38.6  736.21    77.2  735.11
    96.4  732.27   144.7   721.5     164     715   192.9  703.46   212.2  697.45
   289.4   681.7   337.4  679.03     347  677.71   356.5  675.25   375.6  668.49
   385.2  666.27   394.8  666.11   404.3  667.43   423.4  670.92   471.2  674.14
   480.8  675.86   509.4  682.49   538.1   691.3   566.8  698.52   662.4  707.49
   681.5  710.42   710.2  716.45   748.4  719.82     758  721.36   767.5  724.09
#Mann= 3 , 0 , 0
       0      .1       0   375.6    .045       0   404.3      .1       0
Bank Sta=375.6,404.3
XS Rating Curve= 0 ,0
Exp/Cntr=0.3,0.1

Type RM Length L Ch R = 1 ,34143.4 ,418.1,437.1,456.4
XS GIS Cut Line= 3
     1487322.685      314245.952     1487761.053      314239.442
     1487908.623      314269.824
#Sta/Elev= 30
       0  763.03    58.5  737.99    68.2  734.47   107.2  726.08   116.9  724.43
   136.4  721.97   146.1  719.69   155.9  715.74   165.6  710.04   185.1  697.14
   214.3  675.61   224.1   670.5   233.8  668.71   243.6  668.37     341  668.49
   360.5  666.41   370.2   665.4     380   665.5   389.7  666.85   399.4  669.61
   428.7   683.8   447.8  691.21   457.2  694.45   466.7  697.09   485.5  700.64
   494.9  703.24   513.8  709.75     542  720.17   570.2  729.04   589.1  735.78
#Mann= 3 , 0 , 0
       0      .1       0   360.5    .045       0   389.7      .1       0
Bank Sta=360.5,389.7
XS Rating Curve= 0 ,0
Exp/Cntr=0.3,0.1

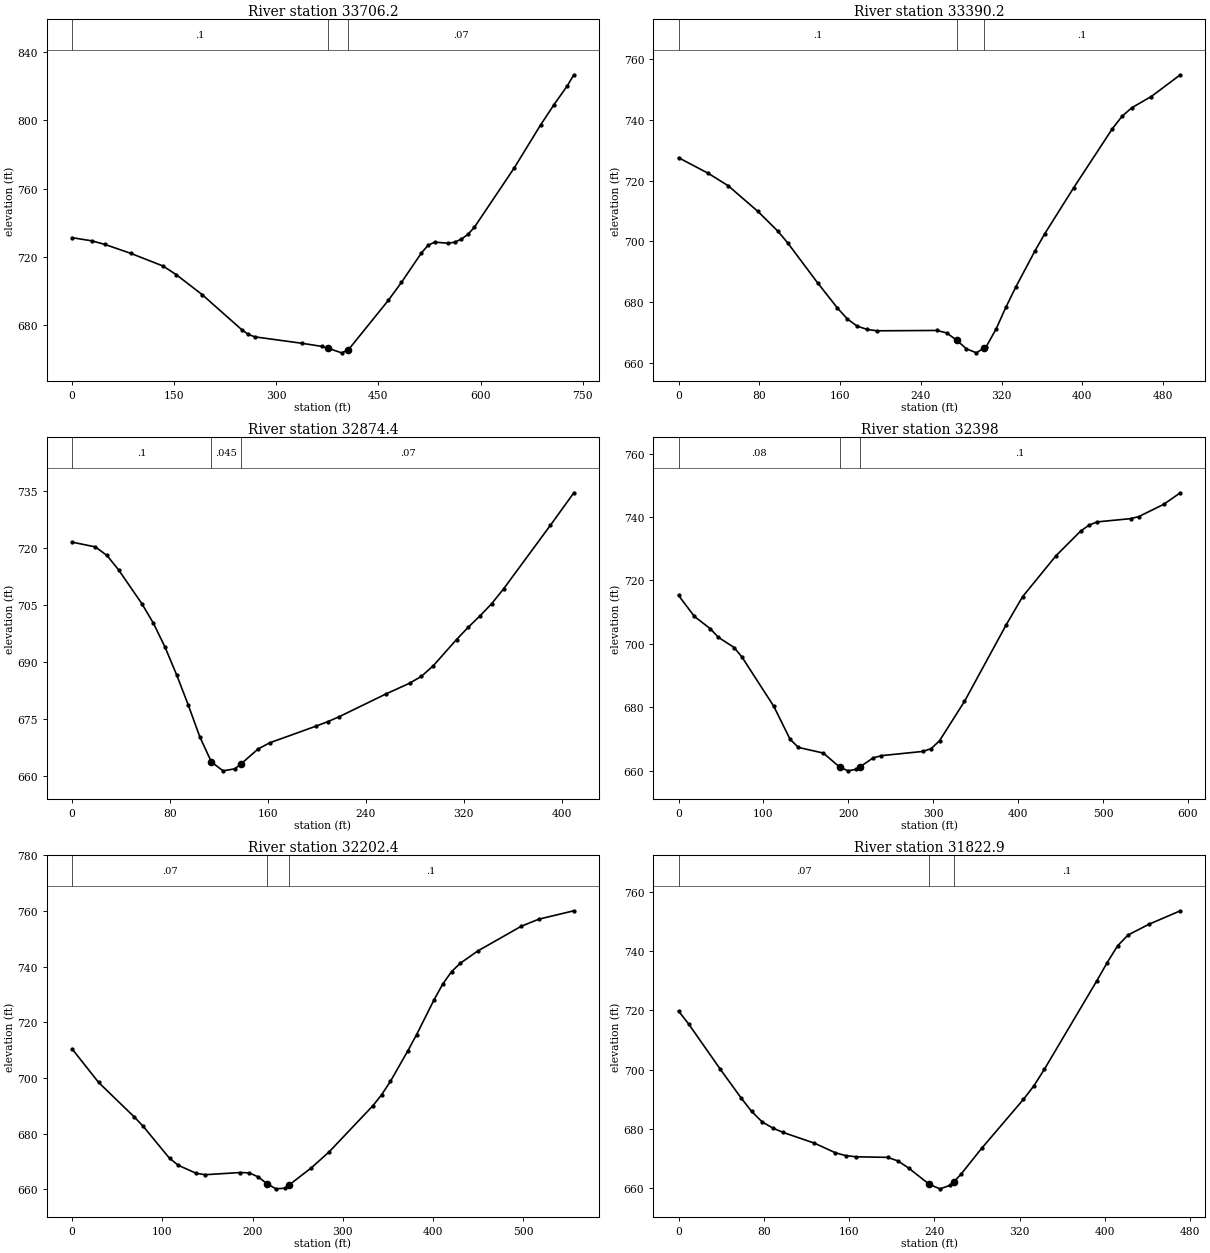
Type RM Length L Ch R = 1 ,33706.2 ,299.8,316.1,332.5
XS GIS Cut Line= 4
     1487368.258      314354.459     1487502.807       314528.07
     1487661.227      314701.681      1487865.22      314896.994
#Sta/Elev= 30
       0  731.15    28.6  729.32    47.8  727.24      86  721.97   133.7  714.48
   152.8   709.5     191  697.72     249  677.18   258.8  674.33   268.6  672.88
   337.2  669.13   366.5   667.3   376.3  666.16   395.9  663.49   405.7  665.17
   464.4  694.26   483.9  704.91   513.1  722.14   522.8  726.62   532.6  728.54
   552.1   727.9   561.8  728.46   571.5  730.23   581.3  733.02     591  737.27
   649.4  772.07   688.4  797.49   707.9   809.3   727.4  820.34   737.1  826.86
#Mann= 3 , 0 , 0
       0      .1       0   376.3    .045       0   405.7     .07       0
Bank Sta=376.3,405.7
XS Rating Curve= 0 ,0
Exp/Cntr=0.3,0.1

Type RM Length L Ch R = 1 ,33390.2 ,510.9,515.8,519.8
XS GIS Cut Line= 3
     1487324.856      314432.584     1487331.366      314747.254
     1487327.026      314929.546
#Sta/Elev= 30
       0  727.61    29.5  722.44    49.2  718.36    78.7  709.88    98.4  703.39
   108.2   699.5   137.7  686.39   157.4  678.07   167.2  674.47     177  672.08
   186.9  670.99   196.7  670.55   255.7  670.67   265.6  669.87   275.4  667.49
   285.2  664.61   295.1  663.29   302.4  664.83   304.9  665.36   314.7  671.22
   324.3  678.32   333.9  684.85   353.1  696.89   362.7  702.49   391.5  717.73
   429.9  737.22   439.5   741.3   449.1  744.08   468.3  747.76   497.1  754.93
#Mann= 3 , 0 , 0
       0      .1       0   275.4    .045       0   302.4      .1       0
Bank Sta=275.4,302.4
XS Rating Curve= 0 ,0
Exp/Cntr=0.3,0.1

Type RM Length L Ch R = 1 ,32874.4 ,484.6,476.4,467.6
XS GIS Cut Line= 3
     1486864.786      314469.476     1486825.724       314684.32
     1486843.085      314875.292
#Sta/Elev= 30
       0  721.48      19  720.23    28.5  717.98      38  714.21      57  705.32
    66.5  700.16      76  693.87    85.4  686.65    94.9  678.74   104.4  670.31
   113.9   663.7   123.4  661.38   132.9   661.9  138.37  663.27   151.9  667.09
   161.4  668.73   199.4  673.13   208.9  674.29   218.4  675.62   256.7  681.61
   275.9  684.41   285.5  686.22   295.1  688.96   314.2  695.88   323.8  699.12
   333.4   702.1     343  705.33   352.6  709.17     391  725.94   410.1  734.45
#Mann= 3 , 0 , 0
       0      .1       0   113.9    .045       0  138.37     .07       0
Bank Sta=113.9,138.37
XS Rating Curve= 0 ,0
Exp/Cntr=0.3,0.1

Type RM Length L Ch R = 1 ,32398   ,184.5,195.6,206.7
XS GIS Cut Line= 3
     1486365.654      314484.667     1486369.994      314606.195
      1486463.31      315066.265
#Sta/Elev= 30
       0  715.29    18.7  708.66    37.4  704.79    46.8   702.1    65.5  698.85
    74.8  695.82   112.2   680.3   131.4  669.91   141.2  667.34   170.5  665.57
   190.1  661.07   199.8  659.96   209.6  660.47  213.67  661.22   229.2  664.03
     239  664.75   287.9  666.09   297.6  666.98   307.4  669.45   336.8  681.87
   385.7  705.91   405.2  714.88   444.3  727.72   473.7   735.6   483.5  737.46
   493.2  738.48   532.4   739.5   542.1  740.15   571.5  744.03     591  747.66
#Mann= 3 , 0 , 0
       0     .08       0   190.1    .045       0  213.67      .1       0
Bank Sta=190.1,213.67
XS Rating Curve= 0 ,0
Exp/Cntr=0.3,0.1

Type RM Length L Ch R = 1 ,32202.4 ,370.5,379.5,387.9
XS GIS Cut Line= 3
     1486265.828      314502.029     1486181.192      314784.147
     1486035.793       315001.16
#Sta/Elev= 30
       0  710.47    29.4  698.42    68.7   686.1    78.5  682.78     108  671.17
   117.8  668.66   137.4  665.82   147.3   665.3   186.5  666.09   196.4  665.94
   206.2  664.51     216  662.05   225.8  660.23   235.6  660.45   239.9  661.49
   265.1  667.79   284.7  673.49   333.2  690.07   342.9  694.02   352.6   698.8
   371.9  709.77   381.6  715.59     401  728.11   410.6  733.76   420.3  738.19
     430   741.2   449.3   745.6   497.7  754.51   517.1  757.04   555.8  760.04
#Mann= 3 , 0 , 0
       0     .07       0     216    .045       0   239.9      .1       0
Bank Sta=216,239.9
XS Rating Curve= 0 ,0
Exp/Cntr=0.3,0.1

Type RM Length L Ch R = 1 ,31822.9 ,550.7,549.3,547.1
XS GIS Cut Line= 2
     1486020.602       314369.65     1485725.463      314736.404
#Sta/Elev= 30
       0  719.78     9.8  715.26    39.2  700.15    58.8  690.44    68.6  685.92
    78.5   682.4    88.3  680.36    98.1  678.86   127.5  675.24   147.1  672.01
   156.9  671.03   166.7  670.64   196.2  670.45     206  669.23   215.8  666.86
   235.3  661.35   245.2  659.84     255  661.04  258.27   662.2   264.8  664.68
   284.4   673.5   323.6     690   333.5  694.62   343.3  700.18   392.3  729.88
   402.1  736.06   411.9  741.74   421.7   745.4   441.3  749.02   470.8  753.58
#Mann= 3 , 0 , 0
       0     .07       0   235.3    .045       0  258.27      .1       0
Bank Sta=235.3,258.27
XS Rating Curve= 0 ,0
Exp/Cntr=0.3,0.1

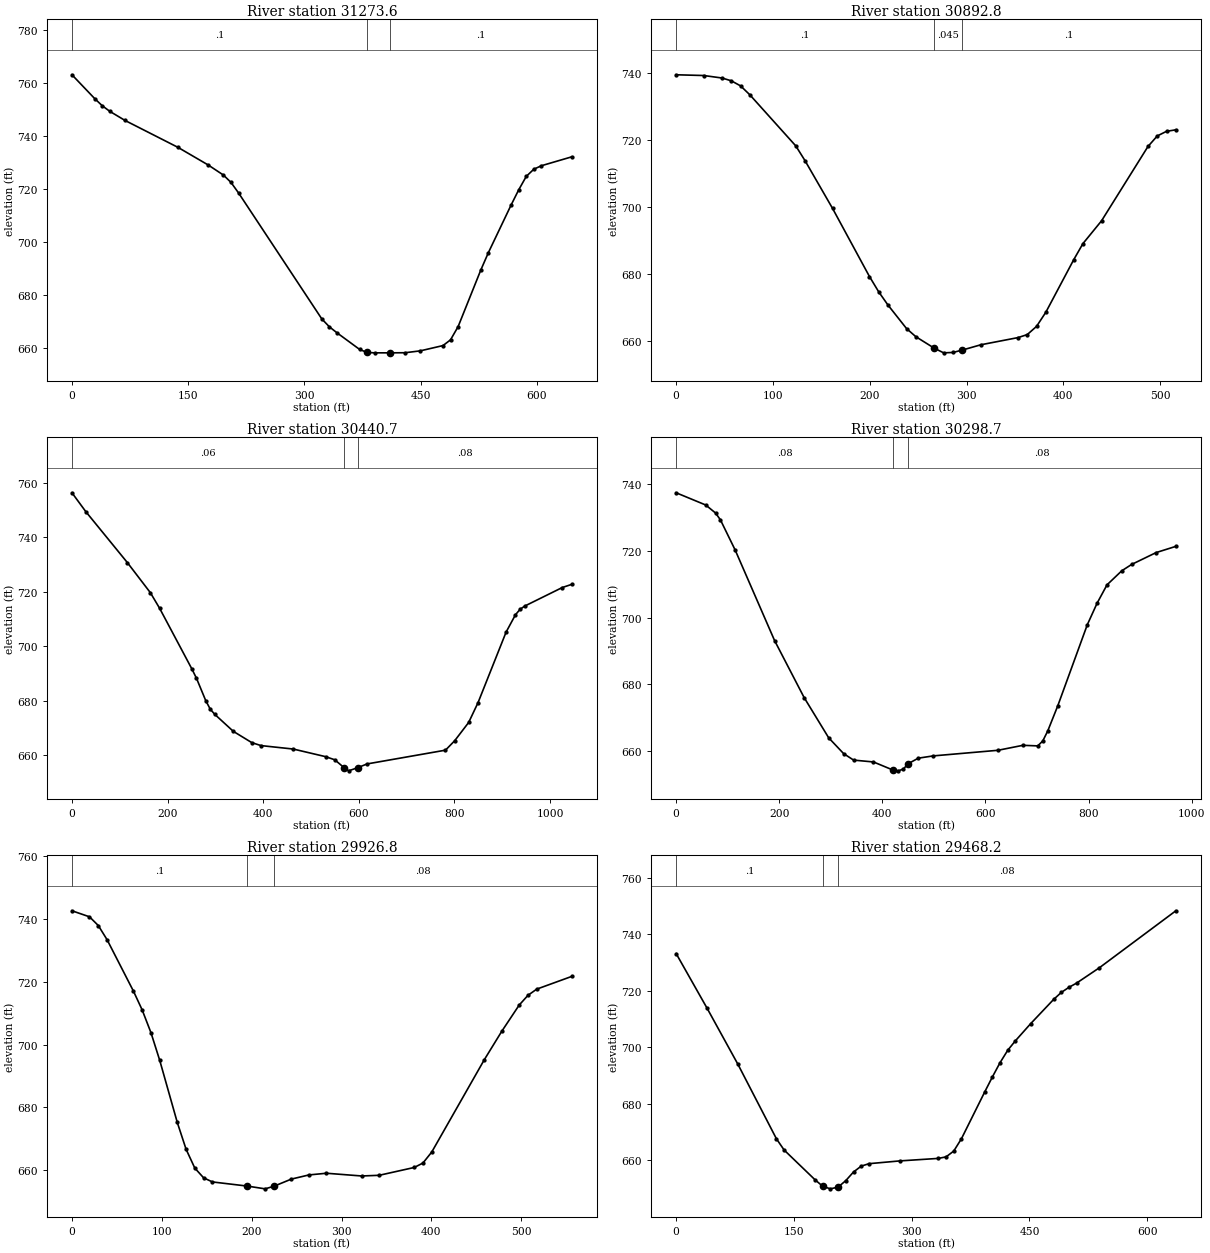
Type RM Length L Ch R = 1 ,31273.6 ,388.4,380.8,372.1
XS GIS Cut Line= 2
      1485673.38      313887.879     1485311.401      314421.733
#Sta/Elev= 30
       0  763.16    29.3  754.19    39.1  751.48    48.9  749.36    68.4  745.95
   136.8  735.79   175.9  729.13   195.5  725.34   205.2  722.59     215  718.61
   322.5  671.08   332.3   668.1     342  665.87   371.4  659.56   381.1  658.43
   390.9   658.3   410.5   658.3     430  658.34   449.6  659.05   478.9  661.04
   488.6   663.2   498.4  668.18   527.7  689.53   537.5   696.1   566.8  714.04
   576.6  719.76   586.4  724.85   596.1  727.54   605.9  728.86     645  732.21
#Mann= 3 , 0 , 0
       0      .1       0   381.1    .045       0   410.5      .1       0
Bank Sta=381.1,410.5
XS Rating Curve= 0 ,0
Exp/Cntr=0.3,0.1

Type RM Length L Ch R = 1 ,30892.8 ,475,452.2,430
XS GIS Cut Line= 3
     1485228.067      313734.233     1485160.359       313932.15
     1485082.234      314229.025
#Sta/Elev= 30
       0  739.42    28.5   739.2    47.5  738.45      57  737.62    66.6   736.1
    76.1  733.46   123.6  718.22   133.1  713.84   161.6  699.58   199.7   679.3
   209.2  674.76   218.8  670.81     238   663.8   247.6  661.38   266.7  657.94
   276.3  656.57   285.9  656.68   295.5  657.39   314.7  658.97   353.1  661.11
   362.7  662.01   372.3  664.46   381.9  668.68   410.6  684.28   420.2  689.12
   439.4   695.9   487.4  718.06     497   721.2   506.6  722.58   516.2  723.02
#Mann= 3 , 0 , 0
       0      .1       0   266.7    .045       0   295.5      .1       0
Bank Sta=266.7,295.5
XS Rating Curve= 0 ,0
Exp/Cntr=0.3,0.1

Type RM Length L Ch R = 1 ,30440.7 ,150.1,142,134
XS GIS Cut Line= 4
     1484439.005      313442.567     1484566.609        313775.9
     1484873.901      314109.233     1485056.192      314257.671
#Sta/Elev= 30
       0  756.42    28.9   749.5   115.8  730.78     164   719.7   183.3  713.98
   250.8  691.68   260.5  688.23   279.8  680.04   289.4  676.85     299  674.93
   337.6  668.72   376.2  664.58   395.5  663.49     463  662.22   530.6  659.42
   549.8  658.27   569.1   655.4   578.8  654.21   598.1   655.4   617.4  656.75
   781.4  661.81   800.6  665.27   829.9     672   849.5  679.28   908.2  705.21
   927.8  711.59   937.6  713.61   947.4   714.8  1025.8   721.6  1045.4  722.75
#Mann= 3 , 0 , 0
       0     .06       0   569.1    .045       0   598.1     .08       0
Bank Sta=569.1,598.1
XS Rating Curve= 0 ,0
Exp/Cntr=0.3,0.1

Type RM Length L Ch R = 1 ,30298.7 ,385.7,371.8,357.4
XS GIS Cut Line= 4
     1484181.192      313926.942     1484475.463      313958.192
      1484892.13      314161.317     1485058.797      314288.921
#Sta/Elev= 30
       0  737.41    57.3  733.75    76.4  731.35    85.9  729.29   114.6  720.21
   190.9  693.12   248.2  676.04   295.9  663.96   324.9  659.22   344.2  657.28
   382.8  656.72   421.5  654.24   431.1  654.06   440.8  654.61   450.4  656.23
   469.8  657.86   498.7  658.54   624.3  660.22   672.6  661.71   701.5  661.54
   711.2  663.02   720.8     666   740.2  673.51   797.6  697.86   816.7  704.35
   835.8  709.81   864.4  714.02   883.5  715.92   931.2  719.49   969.4  721.35
#Mann= 3 , 0 , 0
       0     .08       0   421.5    .045       0   450.4     .08       0
Bank Sta=421.5,450.4
XS Rating Curve= 0 ,0
Exp/Cntr=0.3,0.1

Type RM Length L Ch R = 1 ,29926.8 ,458.6,458.6,458.2
XS GIS Cut Line= 3
     1484524.942      314374.858     1484928.588      314301.942
     1485074.422       314307.15
#Sta/Elev= 30
       0  742.68    19.5  740.76    29.3  737.98    39.1  733.45    68.4  717.08
    78.1   711.1    87.9  703.84    97.7  694.98   117.2  675.23     127  666.68
   136.7  660.68   146.5  657.58   156.3  656.27   195.3  654.94   214.9  654.07
   224.6  654.88   244.2  657.18   263.7   658.5   283.2  659.04   322.3  658.17
   341.8  658.38   380.9  660.88   390.6   662.3   400.4  665.81   458.8  695.19
   478.3  704.28   497.7  712.64   507.5  715.75   517.2  717.71   556.1  721.76
#Mann= 3 , 0 , 0
       0      .1       0   195.3    .045       0   224.6     .08       0
Bank Sta=195.3,224.6
XS Rating Curve= 0 ,0
Exp/Cntr=0.3,0.1

Type RM Length L Ch R = 1 ,29468.2 ,433.6,453,472.2
XS GIS Cut Line= 3
     1484725.463      314791.525     1485139.526      314708.192
     1485347.859      314757.671
#Sta/Elev= 30
       0  733.13    39.3  713.84    78.6     694   127.7  667.62   137.5  663.64
   176.8  653.13   186.6  650.82   196.4   649.9   206.3  650.51   216.1  652.82
   225.9  655.86   235.7  657.93   245.6   658.8   284.8  659.78     334  660.67
   343.8  661.21   353.6  663.27   363.4  667.64   392.9  684.11   402.7  689.44
   412.5  694.51   422.4  698.95   432.1  702.27   451.6  708.35   480.8  716.91
   490.5  719.37   500.2  721.17     510  722.68   539.2  728.14   636.5  748.27
#Mann= 3 , 0 , 0
       0      .1       0   186.6    .045       0   206.3     .08       0
Bank Sta=186.6,206.3
XS Rating Curve= 0 ,0
Exp/Cntr=0.3,0.1

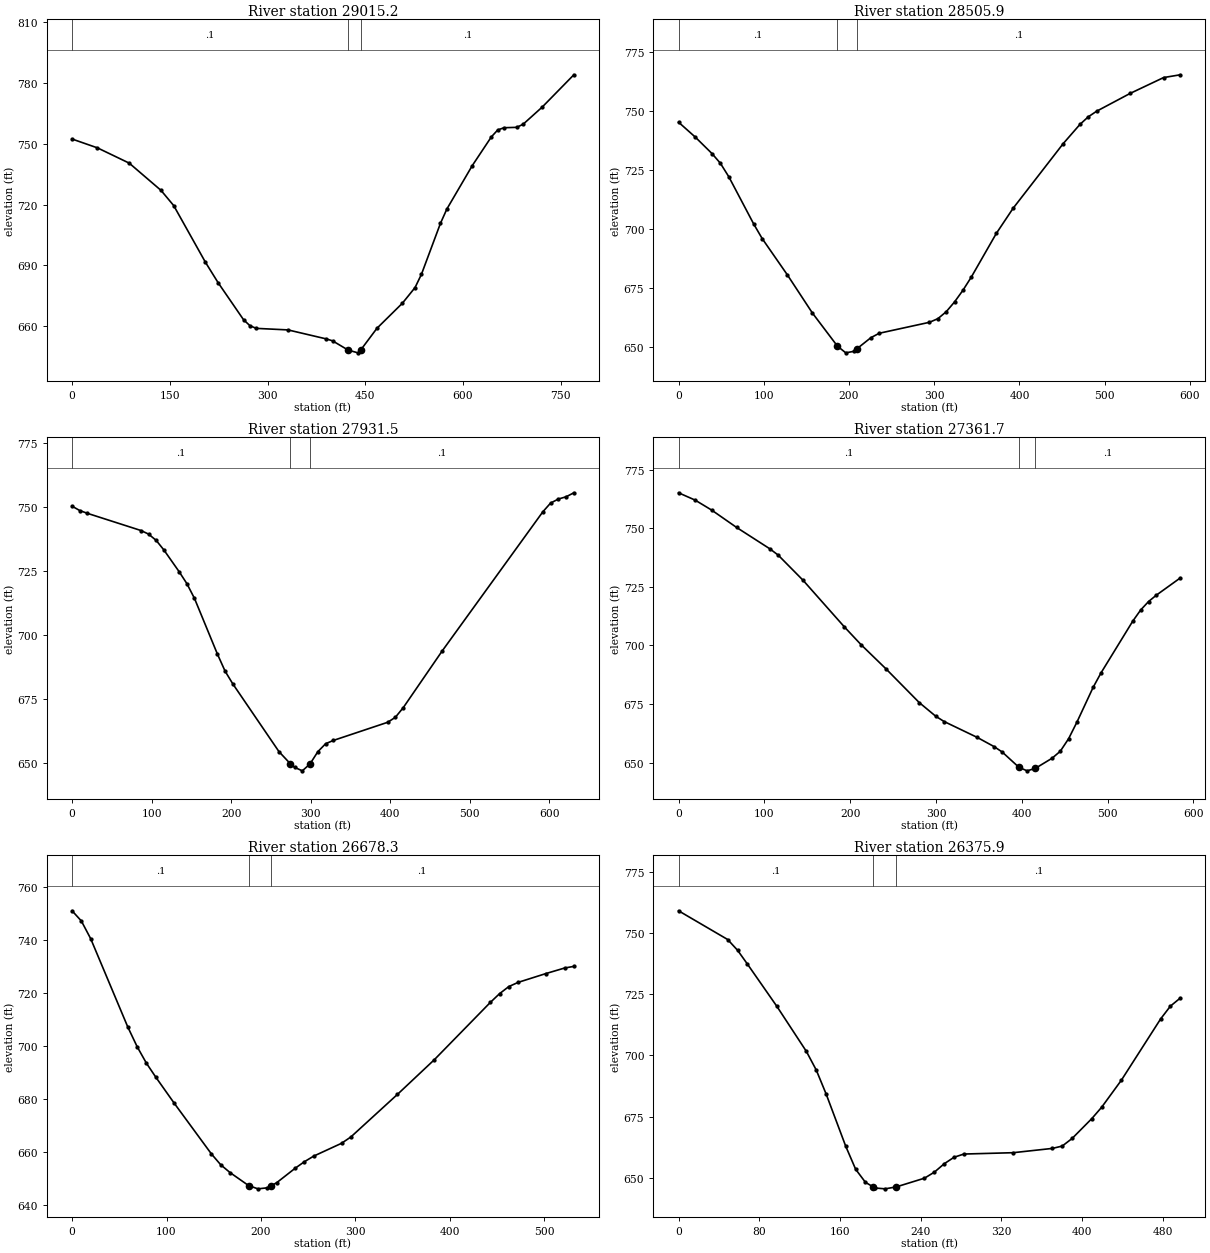
Type RM Length L Ch R = 1 ,29015.2 ,489.6,509.3,529.2
XS GIS Cut Line= 2
      1484691.53      314909.243     1485300.984      315380.067
#Sta/Elev= 30
       0  752.38      39  748.01    87.7  740.49   136.5  727.05     156  719.54
   204.7  691.58   224.2  681.48   263.2  663.23     273  660.29   282.7  658.98
   331.4  658.22   389.9   653.8   399.7  652.84  423.69  648.27   438.7  646.91
   443.4  648.49   467.9  659.02   506.9  671.37   526.4  679.12   536.2  685.66
   565.4  710.82   575.2  717.85   614.2  739.27   643.4   753.4   653.2  756.84
   662.9  757.95   682.4  758.14   692.2  759.66   721.4   768.1   770.1  784.07
#Mann= 3 , 0 , 0
       0      .1       0  423.69    .045       0   443.4      .1       0
Bank Sta=423.69,443.4
XS Rating Curve= 0 ,0
Exp/Cntr=0.3,0.1

Type RM Length L Ch R = 1 ,28505.9 ,578.9,574.4,569.4
XS GIS Cut Line= 2
     1484569.213      314979.025     1484582.234      315567.567
#Sta/Elev= 30
       0   745.2    19.6  738.89    39.2  731.91    49.1  727.77    58.9   722.1
    88.3  701.93    98.1  695.84   127.6  680.47     157  664.27   186.4  650.21
   196.2  647.35     206  648.01  209.58  649.16   225.7  653.79   235.5  655.66
   294.3   660.3   304.2  661.83     314  664.77   323.8  668.94   333.6  673.86
   343.4  679.44   372.8     698   392.5  708.67   451.3  736.11     471  744.28
   480.8   747.5   490.6  749.87   529.8   757.4   569.1  764.13   588.7  765.31
#Mann= 3 , 0 , 0
       0      .1       0   186.4    .045       0  209.58      .1       0
Bank Sta=186.4,209.58
XS Rating Curve= 0 ,0
Exp/Cntr=0.3,0.1

Type RM Length L Ch R = 1 ,27931.5 ,573.1,569.8,566.3
XS GIS Cut Line= 3
     1483962.442      315083.192     1484023.162      315295.914
     1484122.126      315693.432
#Sta/Elev= 30
       0  750.19     9.6   748.5    19.2  747.41    86.6   740.7    96.2   739.3
   105.8  736.83   115.4  733.13   134.6  724.64   144.3     720   153.9  714.22
   182.8  692.45   192.4  685.83     202  680.91   260.2  654.41  274.54  649.67
   279.7  648.32   289.5  646.94   299.2  649.65     309  654.41   318.8  657.52
   328.5   658.8   396.8  665.88   406.5  667.83   416.3  671.55   465.1   693.6
   591.9     748   601.6  751.39   611.4  752.98   621.1  753.85   630.9  755.42
#Mann= 3 , 0 , 0
       0      .1       0  274.54    .045       0   299.2      .1       0
Bank Sta=274.54,299.2
XS Rating Curve= 0 ,0
Exp/Cntr=0.3,0.1

Type RM Length L Ch R = 1 ,27361.7 ,704.7,683.4,661.5
XS GIS Cut Line= 3
     1483389.526      315249.858     1483571.817      315687.358
     1483616.088      315788.921
#Sta/Elev= 30
       0  765.11    19.4  761.97    38.7   757.7    67.7  750.31   106.4   741.2
   116.1  738.52   145.1  727.78   193.4  707.82   212.8  700.26   241.8  689.96
   280.5  675.59   299.8  669.74   309.5   667.5   348.2   660.7   367.6  656.82
   377.2  654.49   396.6  647.99   406.2  646.45   415.9  647.52   435.3  651.82
   444.9  654.81   454.6  660.16   464.3  667.24   483.2  682.09   492.4  688.27
   529.4  710.35   538.6   715.1   547.8  718.71     557  721.46   584.8  728.78
#Mann= 3 , 0 , 0
       0      .1       0   396.6    .045       0   415.9      .1       0
Bank Sta=396.6,415.9
XS Rating Curve= 0 ,0
Exp/Cntr=0.3,0.1

Type RM Length L Ch R = 1 ,26678.3 ,315.1,302.4,289.7
XS GIS Cut Line= 2
     1482728.067      315747.254     1483246.297      315864.442
#Sta/Elev= 30
       0  750.96     9.8  747.13    19.7  740.45      59  707.15    68.9  699.72
    78.7  693.51    88.6  688.26   108.2  678.39   147.6  659.26   157.4   655.2
   167.3  652.25   186.9  647.37   196.8  646.13   206.6  646.51   210.1  647.19
   216.5   648.4   236.1  653.86     246  656.36   255.8  658.46   285.3   663.3
   295.2  665.69   344.4   681.7   383.7  694.86   442.8  716.39   452.6   719.7
   462.4  722.38   472.3  723.97   501.8   727.3   521.5  729.38   531.3     730
#Mann= 3 , 0 , 0
       0      .1       0   186.9    .045       0   210.1      .1       0
Bank Sta=186.9,210.1
XS Rating Curve= 0 ,0
Exp/Cntr=0.3,0.1

Type RM Length L Ch R = 1 ,26375.9 ,458.9,448.5,437.5
XS GIS Cut Line= 2
     1482759.317      316153.504     1483217.651      315960.796
#Sta/Elev= 30
       0  759.15    48.7  747.39    58.5     743    68.2  737.38    97.5  720.02
   126.7  701.62   136.5  693.98   146.2  684.26   165.7  662.81   175.5  653.42
   185.2  648.08  192.84  646.22     195  645.76   204.7  645.42   215.8  646.22
   243.7  649.78   253.5  652.25   263.2  655.66     273  658.34   282.7  659.65
   331.5   660.2   370.5  661.96   380.2  662.92     390  666.03   409.5  674.15
   419.2  678.77   438.7   689.8   477.7  714.93   487.4  720.16   497.2  723.47
#Mann= 3 , 0 , 0
       0      .1       0  192.84    .045       0   215.8      .1       0
Bank Sta=192.84,215.8
XS Rating Curve= 0 ,0
Exp/Cntr=0.3,0.1

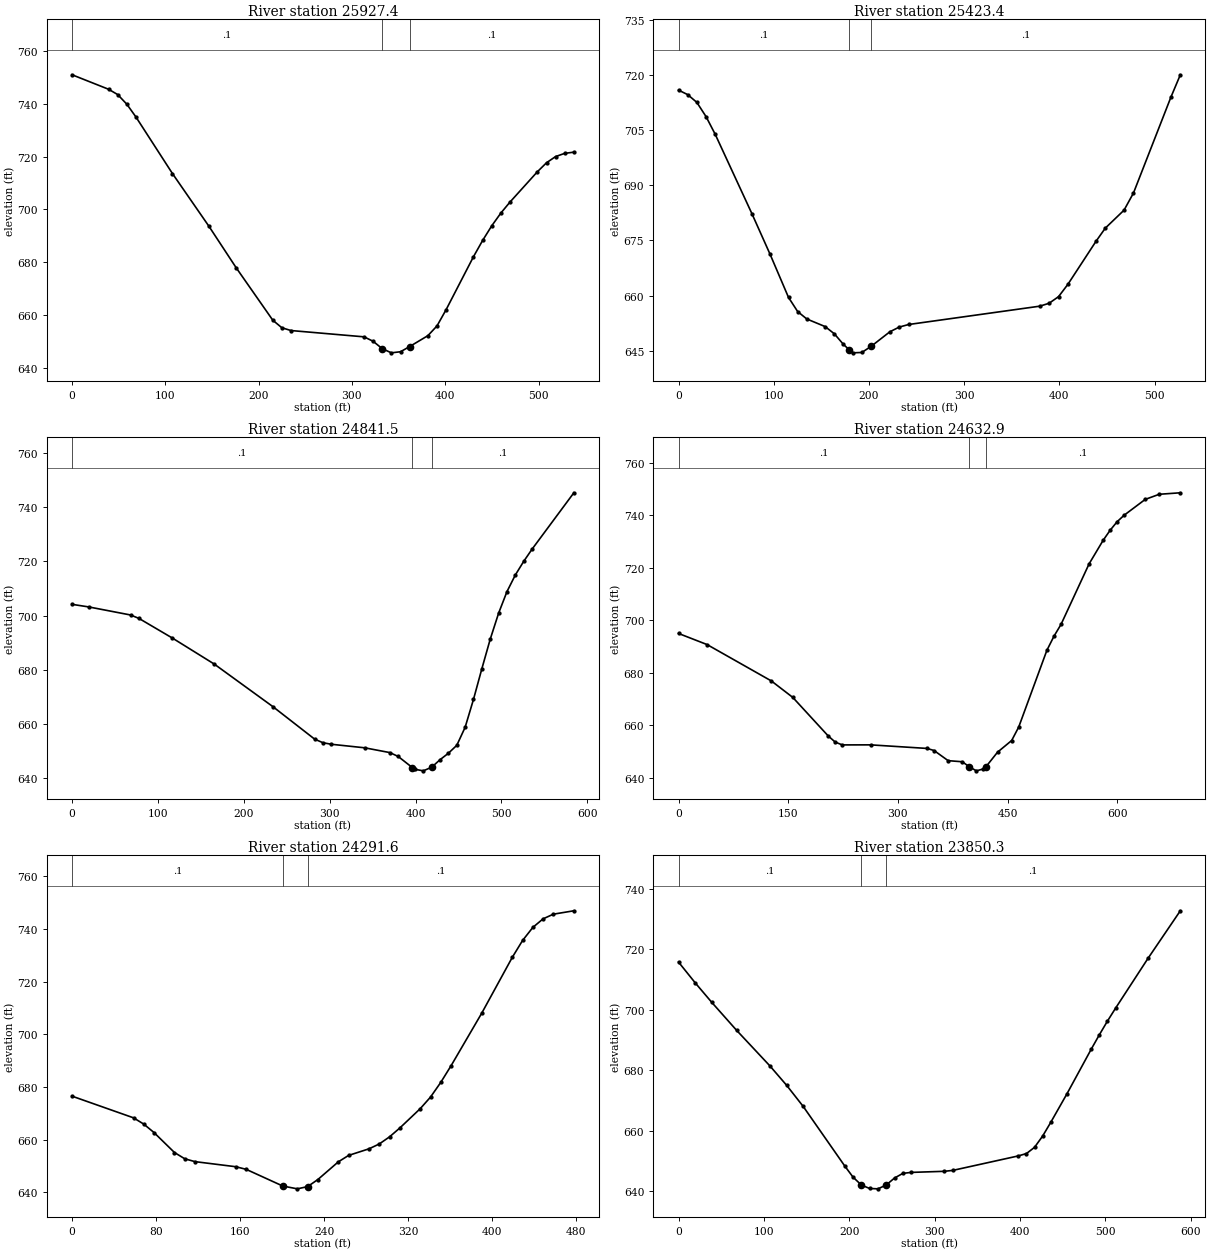
Type RM Length L Ch R = 1 ,25927.4 ,504.1,504.1,502.2
XS GIS Cut Line= 2
     1483095.255       316557.15     1483465.047      316166.525
#Sta/Elev= 30
       0  750.97    39.1  745.49    48.9  743.47    58.7  739.82    68.5  734.96
   107.6  713.55   146.7  693.58     176  677.81   215.2  657.97   224.9  655.12
   234.7  654.07     313  651.68   322.7     650   332.5   647.2   342.3  645.62
   352.1  646.04   361.9  648.01   381.4  652.12   391.2  655.82     401     662
   430.3  682.05   440.1   688.2   449.9  693.76   459.7   698.6   469.4  702.73
   498.8  714.23   508.6  717.64   518.3  719.98   528.1   721.2   537.9  721.65
#Mann= 3 , 0 , 0
       0      .1       0   332.5    .045       0   361.9      .1       0
Bank Sta=332.5,361.9
XS Rating Curve= 0 ,0
Exp/Cntr=0.3,0.1

Type RM Length L Ch R = 1 ,25423.4 ,563.5,581.8,601.5
XS GIS Cut Line= 3
     1483578.328      316779.806     1483710.183      316639.591
      1483919.04      316378.331
#Sta/Elev= 30
       0  715.82     9.6   714.6    19.2   712.5    28.9  708.62    38.5  703.83
      77  682.29    96.2  671.19   115.5   659.5   125.1  655.66   134.7  653.64
     154  651.57   163.6  649.62   173.2  646.73  179.47  645.22   182.8  644.44
   192.5  644.54   202.3  646.21     222  650.17   231.8  651.44   241.7  652.14
   379.4  657.12   389.2  657.91   399.1  659.71   408.9  663.05   438.4  674.73
   448.2  678.32   467.9  683.21   477.8  687.87   517.1   713.9     527  719.99
#Mann= 3 , 0 , 0
       0      .1       0  179.47    .045       0   202.3      .1       0
Bank Sta=179.47,202.3
XS Rating Curve= 0 ,0
Exp/Cntr=0.3,0.1

Type RM Length L Ch R = 1 ,24841.5 ,197.4,208.7,219.8
XS GIS Cut Line= 3
     1483795.342      316849.251     1484034.057      316896.994
     1484374.769      316886.143
#Sta/Elev= 30
       0  704.14    19.5  703.18    68.2   700.2    77.9  698.94   116.8  691.68
   165.5  682.08   233.7  666.37   282.4  654.34   292.1     653   301.9  652.43
   340.8  651.12   370.1  649.35   379.8  647.91  396.12  643.84   399.3  643.17
     409  642.61   418.8  643.97   428.5  646.73   438.2  649.11     448  652.05
   457.7  658.71   467.4  668.99   477.2  680.38   486.9  691.25   496.7  700.89
   506.4  708.84   516.2  715.02   525.9  720.02   535.6  724.52   584.3  745.37
#Mann= 3 , 0 , 0
       0      .1       0  396.12    .045       0   418.8      .1       0
Bank Sta=396.12,418.8
XS Rating Curve= 0 ,0
Exp/Cntr=0.3,0.1

Type RM Length L Ch R = 1 ,24632.9 ,324.3,341.3,358.2
XS GIS Cut Line= 4
     1483804.601      316901.334     1483958.681       316985.97
     1484269.011       317142.22     1484357.986      317278.938
#Sta/Elev= 30
       0  694.89    39.1  690.65     127  676.79   156.3  670.52   204.8  655.82
   214.4  653.48     224  652.42   262.7  652.44   339.9  651.08   349.5  650.29
   368.8  646.42   388.1     646   397.8  644.09   407.4  642.54   417.1  643.27
  420.67  644.15   436.4  649.66   455.7   654.1   465.3  659.21   503.9  688.49
   513.6  693.86   523.2  698.34   561.6  721.41   580.8  730.38   590.4  734.22
     600  737.49   609.6  739.96   638.4  745.98   657.6  747.93   686.4   748.5
#Mann= 3 , 0 , 0
       0      .1       0   397.8    .045       0  420.67      .1       0
Bank Sta=397.8,420.67
XS Rating Curve= 0 ,0
Exp/Cntr=0.3,0.1

Type RM Length L Ch R = 1 ,24291.6 ,437.1,441.3,445.2
XS GIS Cut Line= 2
     1483780.729       316996.82      1483943.49      317446.039
#Sta/Elev= 30
       0  676.47    58.5  668.25    68.3  665.86      78  662.67    97.5  655.08
   107.3   652.7     117  651.62     156  649.68   165.8  648.69  200.68  642.35
   214.5  641.29   224.3  642.14     234  644.81   253.5  651.53   263.3  653.98
   282.8  656.49   292.5  658.32   302.3  661.03     312  664.36   331.5  671.72
   341.3  676.12     351  681.66   360.8  687.97     390  707.92   419.3  729.27
     429  735.59   438.8  740.56   448.5  743.79   458.3  745.56   477.8  746.85
#Mann= 3 , 0 , 0
       0      .1       0  200.68    .045       0   224.3      .1       0
Bank Sta=200.68,224.3
XS Rating Curve= 0 ,0
Exp/Cntr=0.3,0.1

Type RM Length L Ch R = 1 ,23850.3 ,888.5,887.2,885.2
XS GIS Cut Line= 3
     1483377.084       316990.31     1483441.874      317344.545
     1483487.761      317567.567
#Sta/Elev= 30
       0  715.77    19.5  708.92    38.9  702.47    68.1   693.2   107.1  681.45
   126.5  675.11     146   668.1   194.7  648.42   204.4  644.74   214.1  642.15
   223.8  640.99   233.6  640.87   243.3  642.14     253  644.44   262.8  645.98
   272.5   646.3   311.4  646.66   321.2  646.96   398.1  651.75   407.6  652.53
     417  654.58   426.5  658.29     436  662.82     455  672.26   483.4  686.98
   492.9  691.73   502.4  696.26   511.9  700.52   549.9  716.98   587.8  732.71
#Mann= 3 , 0 , 0
       0      .1       0   214.1    .045       0   243.3      .1       0
Bank Sta=214.1,243.3
XS Rating Curve= 0 ,0
Exp/Cntr=0.3,0.1