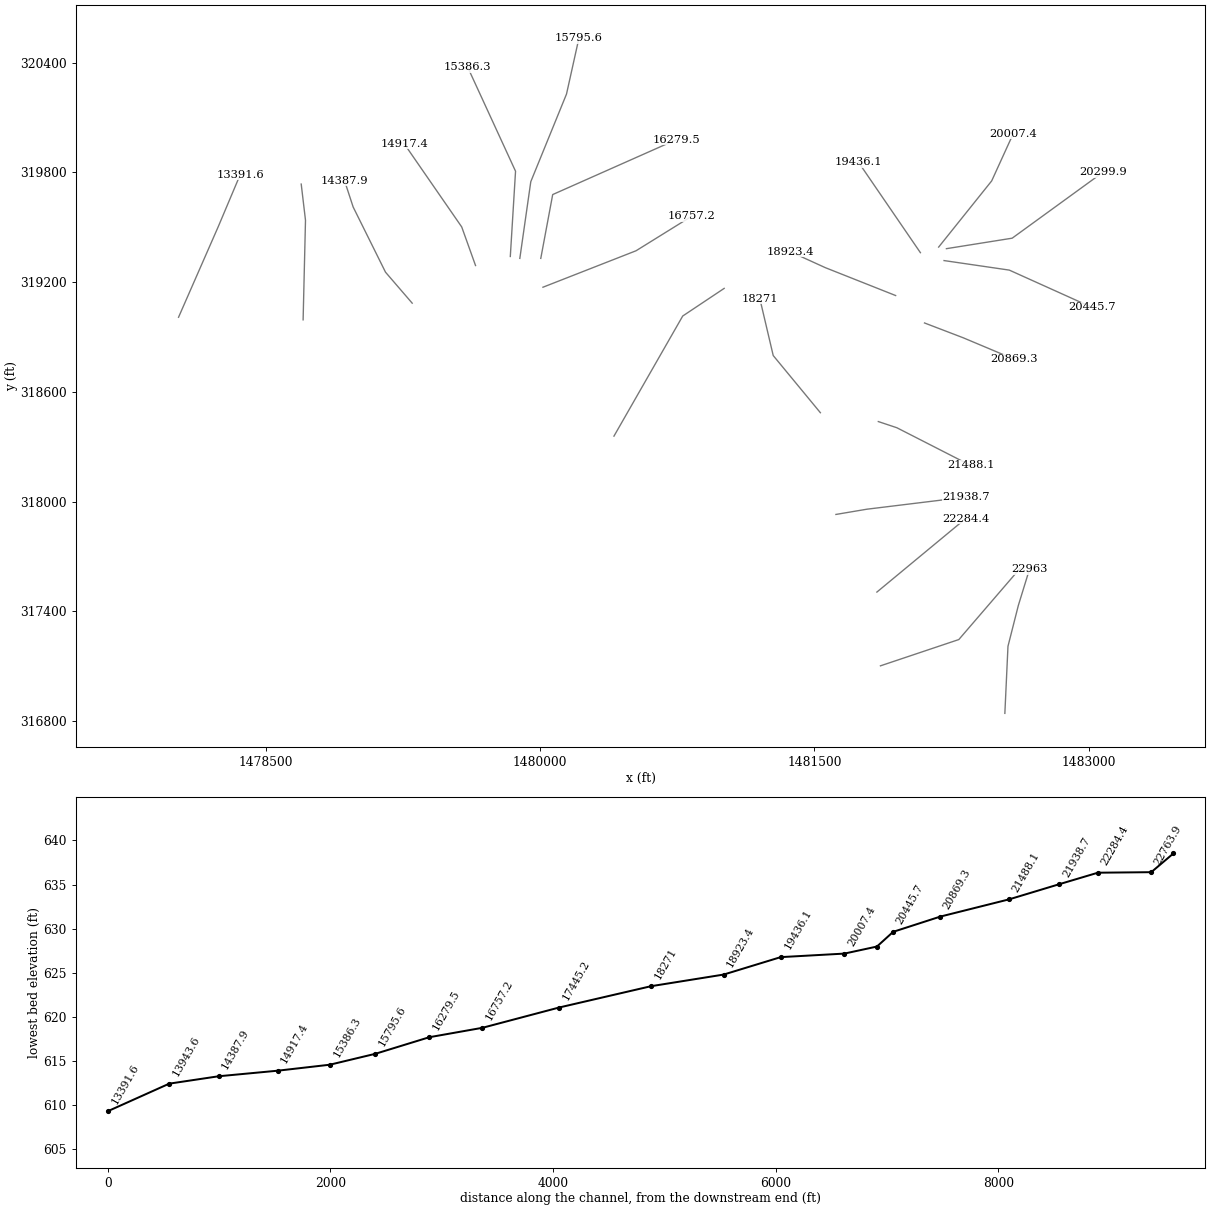
HEC-RAS study FrenchCr.prj: FrenchCr

--- FrenchCr.g01 (geometry) --- (continued)

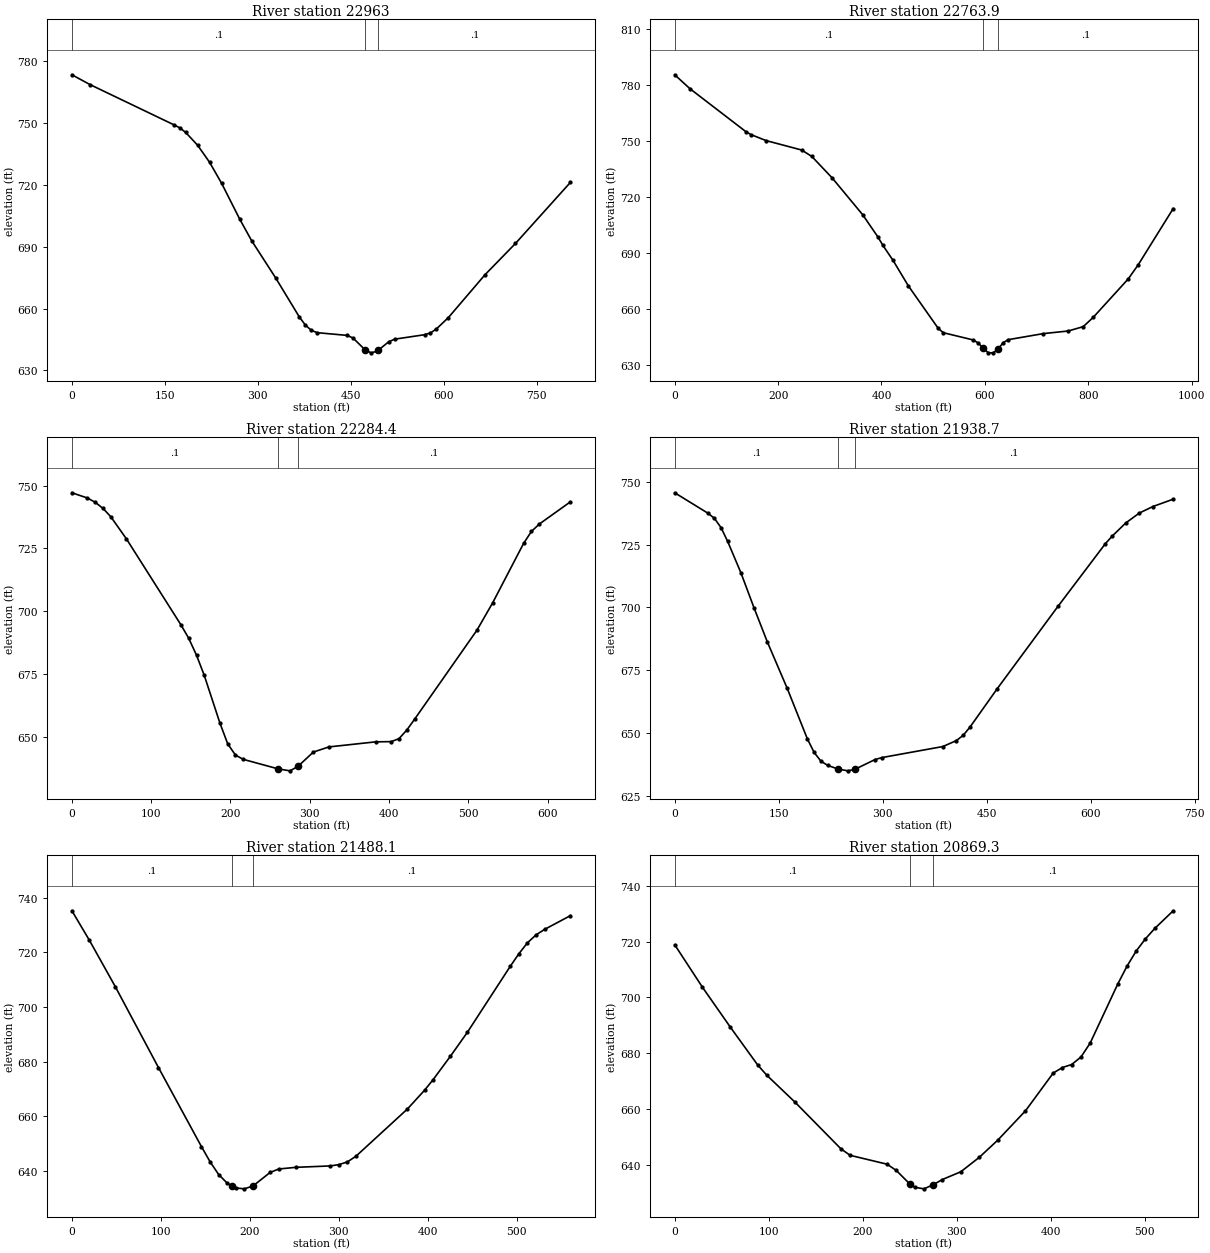
Type RM Length L Ch R = 1 ,22963   ,209.9,199.2,188.6
XS GIS Cut Line= 4
      1482541.58       316842.74     1482558.611      317209.578
     1482615.365      317433.018     1482676.129      317630.501
#Sta/Elev= 30
       0  773.18      29  768.47   164.3     749     174   747.5   183.6  745.27
   202.9  739.04   222.3  730.75   241.6  720.62   270.6   703.4   289.9   692.9
   328.6  674.91   367.2  655.81   376.8  651.96   386.4  649.42     396  648.29
   444.1  646.98   453.7  645.71   472.9  640.04   482.5  638.53   492.1  639.24
  494.65  639.86   511.3   643.9   520.9  645.15     569   647.3   578.6  648.17
   588.2  650.09   607.6  655.63   666.6  676.34   715.8   691.5   804.4  721.06
#Mann= 3 , 0 , 0
       0      .1       0   472.9    .045       0  494.65      .1       0
Bank Sta=472.9,494.65
XS Rating Curve= 0 ,0
Exp/Cntr=0.3,0.1

Type RM Length L Ch R = 1 ,22763.9 ,482.9,479.5,476
XS GIS Cut Line= 3
     1481861.418      317102.661     1482289.844      317246.386
     1482624.045      317634.841
#Sta/Elev= 30
       0  785.28    29.5  777.81   137.5  754.86   147.4  753.26   176.8  750.04
   245.6  744.99   265.2  741.55   304.5  730.07   363.5  710.38     393  698.47
   402.8  693.91   422.4  685.87   451.9  672.28   509.9  649.44   519.6  647.18
   577.6  643.28   587.2  641.64   596.9  638.81   606.6  636.43   616.3   636.4
   625.9  638.56   635.6  641.89   645.3  643.46   712.9  646.69   761.3   648.1
   790.3  650.44   809.6   655.4   877.3  675.98   896.6  683.54   964.3  713.65
#Mann= 3 , 0 , 0
       0      .1       0   596.9    .045       0   625.9      .1       0
Bank Sta=596.9,625.9
XS Rating Curve= 0 ,0
Exp/Cntr=0.3,0.1

Type RM Length L Ch R = 1 ,22284.4 ,358.6,345.7,331.4
XS GIS Cut Line= 2
     1481841.927      317505.935     1482326.302      317906.976
#Sta/Elev= 30
       0  747.13    19.6  745.04    29.5  743.33    39.3  740.88    49.1  737.57
    68.8  728.75   137.6  694.48   147.4  689.12   157.2   682.4     167  674.34
   186.7  655.39   196.5  647.12   206.3  642.62   216.2  640.91   260.3  637.11
   275.1  636.34     285  638.08   304.6  643.82   324.2  645.87   383.2  647.89
   402.9  647.98   412.7  649.18   422.5  652.62   432.3  656.91   510.9  692.36
   530.6  703.19   569.9  727.02   579.7  731.73   589.6  734.67   628.8  743.52
#Mann= 3 , 0 , 0
       0      .1       0   260.3    .045       0     285      .1       0
Bank Sta=260.3,285
XS Rating Curve= 0 ,0
Exp/Cntr=0.3,0.1

Type RM Length L Ch R = 1 ,21938.7 ,463.8,450.5,438.3
XS GIS Cut Line= 3
     1481617.969      317930.414      1481787.24       317959.06
     1482330.212      318025.442
#Sta/Elev= 30
       0  745.56    47.7  737.47    57.2  735.41    66.8   731.7    76.3  726.24
    95.4  713.78   114.4  699.78   133.5   686.3   162.1  667.88   191.2  647.78
     201  642.35   210.8  638.89   220.5  637.21  235.82  635.72   249.8  635.04
   259.6  635.62   288.9  639.54   298.7  640.31   386.6   644.7   406.1  647.06
   415.9  649.16   425.6  652.38   464.7  667.58   552.6  700.43     621  725.37
   630.8  728.35   650.3  733.56   669.8  737.49   689.4  740.09   718.7  743.01
#Mann= 3 , 0 , 0
       0      .1       0  235.82    .045       0   259.6      .1       0
Bank Sta=235.82,259.6
XS Rating Curve= 0 ,0
Exp/Cntr=0.3,0.1

Type RM Length L Ch R = 1 ,21488.1 ,616.7,618.8,620.2
XS GIS Cut Line= 3
      1481849.74      318438.226     1481951.302      318404.372
     1482354.773       318198.23
#Sta/Elev= 30
       0  735.29    19.5  724.56    48.7   707.5    97.3  677.78   145.6  648.78
   155.3  643.22   164.9  638.57   174.5   635.4  179.83   634.3   184.2  633.64
   193.8  633.32   203.5  634.37   222.7  639.33   232.4  640.59   251.7  641.21
   290.2  641.72   299.9  642.19   309.5  643.19   319.1  645.26     377   662.6
   396.3   669.5   405.9  673.38   425.2   681.9   444.5  690.79   492.7     715
   502.3  719.56   511.9  723.56   521.6  726.47   531.2  728.48   560.1   733.5
#Mann= 3 , 0 , 0
       0      .1       0  179.83    .045       0   203.5      .1       0
Bank Sta=179.83,203.5
XS Rating Curve= 0 ,0
Exp/Cntr=0.3,0.1

Type RM Length L Ch R = 1 ,20869.3 ,417.7,423.6,429.2
XS GIS Cut Line= 3
     1482102.344      318977.289     1482313.281       318896.56
     1482594.033       318778.56
#Sta/Elev= 30
       0  718.86    29.5  703.64    58.9  689.46    88.4  675.71    98.2  672.01
   127.7  662.53   176.8  645.72   186.6  643.38   225.9   640.2   235.7  637.97
  250.36  633.03   255.3  631.92   265.2  631.36     275  632.83   284.8   634.7
   304.4  637.48   324.1  642.66   343.7  648.81   373.2  659.32   402.7  672.86
   412.5  674.86   422.3  675.92   432.2   678.6     442  683.58   471.5  704.85
   481.3  711.23   491.1  716.66   500.9  721.01   510.8  724.72   530.4  731.05
#Mann= 3 , 0 , 0
       0      .1       0  250.36    .045       0     275      .1       0
Bank Sta=250.36,275
XS Rating Curve= 0 ,0
Exp/Cntr=0.3,0.1

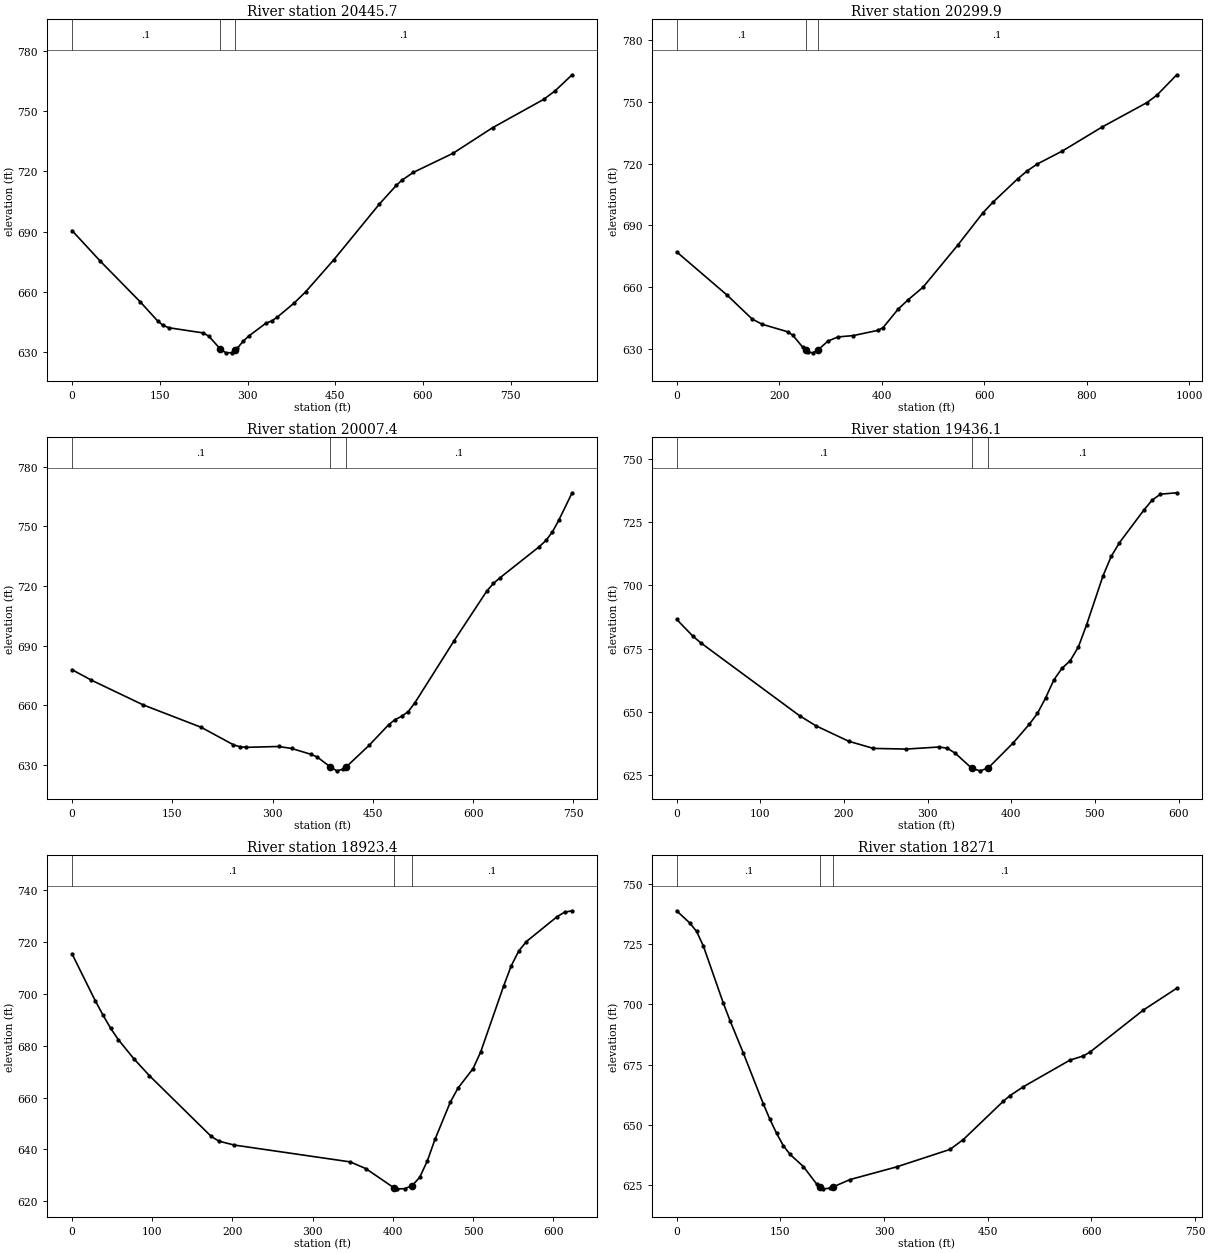
Type RM Length L Ch R = 1 ,20445.7 ,138.9,145.8,152.6
XS GIS Cut Line= 3
     1482209.115      319318.435     1482565.886      319266.351
     1483016.406      319063.226
#Sta/Elev= 30
       0  690.56    48.7   675.2   116.9  654.96   146.2  645.57   155.9  643.29
   165.7  642.12   224.1  639.55   233.9  637.92   253.4  631.57   263.1  629.63
   272.8  629.73  278.36  631.11   282.6  631.97   292.3  635.31   302.1  637.99
   331.3  644.35   341.1   645.5   350.8  647.39   379.9  654.48   399.3     660
   447.8   676.1   525.3  703.71   554.4  713.08     564  715.63   583.4  719.51
   651.3  729.03   719.1  741.81   806.3   755.9   825.7  760.13   854.8  768.13
#Mann= 3 , 0 , 0
       0      .1       0   253.4    .045       0  278.36      .1       0
Bank Sta=253.4,278.36
XS Rating Curve= 0 ,0
Exp/Cntr=0.3,0.1

Type RM Length L Ch R = 1 ,20299.9 ,275.7,292.5,309
XS GIS Cut Line= 3
     1482222.136      319383.539     1482581.511      319440.831
     1483076.302      319800.206
#Sta/Elev= 30
       0  677.05    98.4  656.02   147.5  644.34   167.2  641.83   216.4  638.21
   226.2   636.6   245.9  630.71  252.45  629.15   255.7  628.42   265.6  627.96
   275.4  629.33   295.1  633.68   314.7  635.69   344.2  636.34     393  638.91
   402.7  640.26   431.9  649.18   451.3  653.73   480.4  659.82   548.3  680.33
   596.9  695.89   616.3  701.05   664.8  712.48   684.2  716.52   703.6  719.79
   752.2  726.07   829.8  737.75   917.2  749.61   936.6  753.21   975.4  763.14
#Mann= 3 , 0 , 0
       0      .1       0  252.45    .045       0   275.4      .1       0
Bank Sta=252.45,275.4
XS Rating Curve= 0 ,0
Exp/Cntr=0.3,0.1

Type RM Length L Ch R = 1 ,20007.4 ,542,571.4,599.7
XS GIS Cut Line= 3
     1482179.601       319392.22     1482469.531      319754.025
     1482587.587      320012.706
#Sta/Elev= 30
       0  677.96      29  672.71   106.2  660.32   193.2  649.03   241.5  640.24
   251.1  639.27   260.8  638.97   309.1  639.39   328.4  638.41   357.4  635.46
     367  634.06   386.4  629.12     396  627.16   405.5  627.98  409.89  629.05
   444.3  639.95   473.4  650.26   483.2   652.9   493.1  654.54   502.9  656.95
   512.7  661.26   571.5  692.52   620.5  717.51   630.3   721.3   640.1  724.12
     699  739.79   708.8  742.86   718.6  747.22   728.4  753.28     748  766.82
#Mann= 3 , 0 , 0
       0      .1       0   386.4    .045       0  409.89      .1       0
Bank Sta=386.4,409.89
XS Rating Curve= 0 ,0
Exp/Cntr=0.3,0.1

Type RM Length L Ch R = 1 ,19436.1 ,499.4,512.7,525
XS GIS Cut Line= 2
     1482079.775      319361.664     1481741.998      319855.056
#Sta/Elev= 30
       0  686.54    19.6  679.85    29.4  677.14     147   648.5   166.6  644.52
   205.8  638.43   235.2  635.61   274.5  635.35   313.7  636.17   323.5   635.7
   333.3  633.66   352.9  627.74   362.7  626.76   372.5  627.89   401.9  637.63
   421.5   645.1   431.3  649.41   441.1  655.54   450.9  662.62   460.7  667.24
   470.5  670.21   480.3  675.68   490.1   684.4   509.7  703.69   519.5  711.36
   529.3  716.77   558.7  729.73   568.5   733.6   578.3  735.93   597.9  736.49
#Mann= 3 , 0 , 0
       0      .1       0   352.9    .045       0   372.5      .1       0
Bank Sta=352.9,372.5
XS Rating Curve= 0 ,0
Exp/Cntr=0.3,0.1

Type RM Length L Ch R = 1 ,18923.4 ,663.6,652.4,641.7
XS GIS Cut Line= 3
     1481944.358      319127.289     1481558.939      319280.099
     1481368.837      319366.872
#Sta/Elev= 30
       0  715.51    28.9  697.46    38.6  691.88    48.2  686.75    57.8  682.35
    77.1     675    96.4   668.5   173.6  645.02   183.2  643.18   202.5  641.67
   347.1  635.17   366.4  632.58  400.94  625.29     405  624.78   414.6  624.82
   424.1  626.01   433.6  629.24   443.1  635.59   452.6  643.87   471.6  658.16
   481.1  663.57   500.1   671.2   509.6  677.63   538.1  702.96   547.6   710.8
   557.1   716.6   566.6  720.23   604.6  729.76   614.1  731.56   623.6   732.1
#Mann= 3 , 0 , 0
       0      .1       0  400.94    .045       0   424.1      .1       0
Bank Sta=400.94,424.1
XS Rating Curve= 0 ,0
Exp/Cntr=0.3,0.1

Type RM Length L Ch R = 1 ,18271   ,853,825.8,798.5
XS GIS Cut Line= 3
       1481532.9      318486.664     1481275.087      318799.164
      1481202.17       319109.06
#Sta/Elev= 30
       0  738.88    19.3  733.73    28.9   730.3    38.6  724.32    67.5  700.58
    77.2  693.31    96.5  679.81   125.4  658.71     135  652.28   144.7  646.45
   154.3   641.4     164  637.77   183.3  632.73   202.6  625.44     208  624.33
   212.2  623.46   221.8  623.73  226.51  624.28   250.8  627.31   318.3  632.58
   395.5  639.83   414.8  643.94   472.6  659.84   482.3  662.17   501.6  665.84
   569.1  676.91   588.4  678.63   598.1  680.25   675.2  697.68   723.5  706.73
#Mann= 3 , 0 , 0
       0      .1       0     208    .045       0  226.51      .1       0
Bank Sta=208,226.51
XS Rating Curve= 0 ,0
Exp/Cntr=0.3,0.1

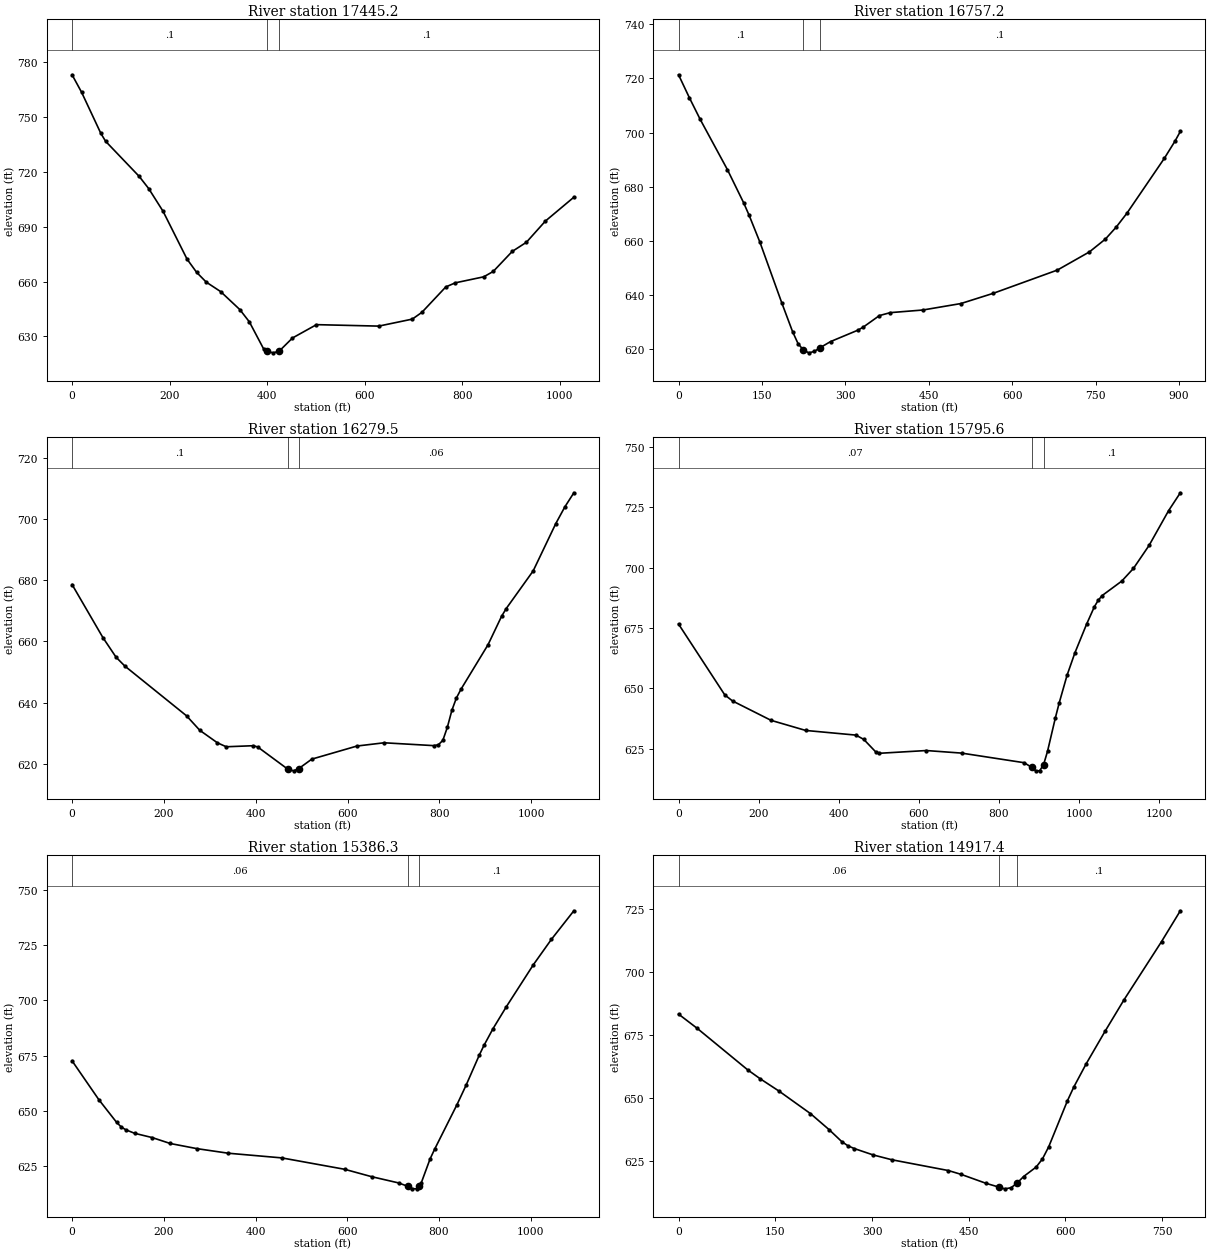
Type RM Length L Ch R = 1 ,17445.2 ,703.3,688,672.8
XS GIS Cut Line= 3
     1480404.351      318358.624     1480780.295       319015.31
     1481006.858      319166.351
#Sta/Elev= 30
       0  773.24    19.6  763.63      59  741.17    68.8  736.83   137.6  717.63
   157.2  710.93   186.7  698.47   235.8  672.33   255.5  665.07   275.2  659.74
   304.6  654.58     344  644.72   363.6  637.98   393.1  623.05  399.35   621.9
   412.7  621.04  425.05  622.05     452  629.17   501.2  636.47   628.9  635.67
   697.7   639.5   717.4  643.21   766.4  657.12   785.9  659.36   844.2  662.65
   863.7   665.6   902.6  676.54   931.7  681.56   970.6  693.16    1029  706.22
#Mann= 3 , 0 , 0
       0      .1       0  399.35    .045       0  425.05      .1       0
Bank Sta=399.35,425.05
XS Rating Curve= 0 ,0
Exp/Cntr=0.3,0.1

Type RM Length L Ch R = 1 ,16757.2 ,476,477.6,479.3
XS GIS Cut Line= 3
     1480016.084      319172.757     1480525.087      319372.081
      1480827.17      319559.581
#Sta/Elev= 30
       0  721.32    19.5  712.85      39  704.84    87.8  686.36   117.1  674.08
   126.9  669.49   146.4  659.52   185.5  637.25     205  626.58   214.8  622.18
   224.5  619.76   234.3  618.74     244  619.25   253.8  620.55   273.3  622.89
   322.1  627.07   331.9   628.2   361.2  632.49   380.7  633.57   439.3  634.54
   507.6  636.92   565.9   640.7   681.2  649.28   738.8  655.98   767.6  660.73
   786.9  665.12   806.1  670.22   873.4  690.48   892.6  696.83   902.2  700.41
#Mann= 3 , 0 , 0
       0      .1       0   224.5    .045       0   253.8      .1       0
Bank Sta=224.5,253.8
XS Rating Curve= 0 ,0
Exp/Cntr=0.3,0.1

Type RM Length L Ch R = 1 ,16279.5 ,466.9,483.9,500.6
XS GIS Cut Line= 3
     1480004.254      319330.414     1480069.358      319679.372
     1480743.837      319978.851
#Sta/Elev= 30
       0  678.57    67.2  661.22    95.9   654.8   115.1   651.9   249.4  635.65
   278.2  630.92   316.6  626.83   335.8  625.54   394.3  625.88   404.2  625.49
  469.93  618.21   482.9  617.67   493.8  618.41   522.2   621.5   620.6  625.78
   679.7  626.84   787.9  625.91   797.8  626.18   807.6  627.63   817.4  631.88
   827.3  637.46   837.1  641.47     847  644.31     906  658.88   935.5  668.16
   945.4  670.66  1004.4  683.03  1053.6  698.48  1073.3  703.93    1093  708.56
#Mann= 3 , 0 , 0
       0      .1       0  469.93    .045       0   493.8     .06       0
Bank Sta=469.93,493.8
XS Rating Curve= 0 ,0
Exp/Cntr=0.3,0.1

Type RM Length L Ch R = 1 ,15795.6 ,391.2,409.3,427.9
XS GIS Cut Line= 4
      1479889.67      319330.414     1479949.566      319749.685
     1480144.879      320228.851     1480212.587      320533.539
#Sta/Elev= 30
       0  676.59   115.5  647.24   134.8  644.74     231  636.71   317.6  632.52
     443  630.59   462.6  628.81   491.9  623.73   501.6  623.06   618.8   624.2
   706.7  623.14   862.9  619.16   882.4  617.21   892.2  615.79   901.9  615.82
   911.7  618.41   921.4  623.84     941  637.71   950.7  643.98   970.2  655.36
   989.7  664.62    1019  676.54  1038.5  683.78  1048.3   686.5    1058  688.41
  1106.8  694.38    1136  699.63  1175.1  709.17  1223.8  723.56  1253.1  730.97
#Mann= 3 , 0 , 0
       0     .07       0   882.4    .045       0   911.7      .1       0
Bank Sta=882.4,911.7
XS Rating Curve= 0 ,0
Exp/Cntr=0.3,0.1

Type RM Length L Ch R = 1 ,15386.3 ,464.5,468.9,472.6
XS GIS Cut Line= 3
     1479837.587      319340.831     1479866.233      319806.976
     1479604.147      320376.656
#Sta/Elev= 30
       0  672.59    58.4  654.97    97.3  644.64     107  642.64   116.8  641.36
   136.2  639.74   175.1  637.77     214  635.11   272.4  632.77   340.5   630.7
   457.3  628.58   594.4  623.41   653.2  620.06     712  617.23   731.6  615.73
   741.4  614.62   751.2  614.55  756.66  615.92     761  617.05   780.6  628.11
   790.4  632.46   839.4  652.77     859  661.48   888.3  675.37   898.1  679.58
   917.7  687.12   947.1  697.19  1005.9  716.19  1045.1  727.65  1094.1  740.62
#Mann= 3 , 0 , 0
       0     .06       0   731.6    .045       0  756.66      .1       0
Bank Sta=731.6,756.66
XS Rating Curve= 0 ,0
Exp/Cntr=0.3,0.1

Type RM Length L Ch R = 1 ,14917.4 ,532.8,529.5,526.3
XS GIS Cut Line= 3
     1479647.483      319291.351     1479571.962      319502.289
     1479256.858      319958.018
#Sta/Elev= 30
       0  683.25    29.2  677.54   107.2  661.12   126.6  657.58   155.9  652.66
   204.6  643.74   233.8   637.3   253.2   632.6   262.9  630.93   272.6  629.86
   301.8  627.33     331   625.4   418.5  621.13   437.9  619.64   476.8  616.06
   496.2   614.6   505.9  613.87   515.7  614.31   525.4  616.26   535.1  618.76
   554.5  622.51   564.3  625.74     574  630.56   603.1  648.88   612.9  654.28
   632.3   663.6   661.5  676.48   690.6  688.85     749  712.05   778.1  724.27
#Mann= 3 , 0 , 0
       0     .06       0   496.2    .045       0   525.4      .1       0
Bank Sta=496.2,525.4
XS Rating Curve= 0 ,0
Exp/Cntr=0.3,0.1

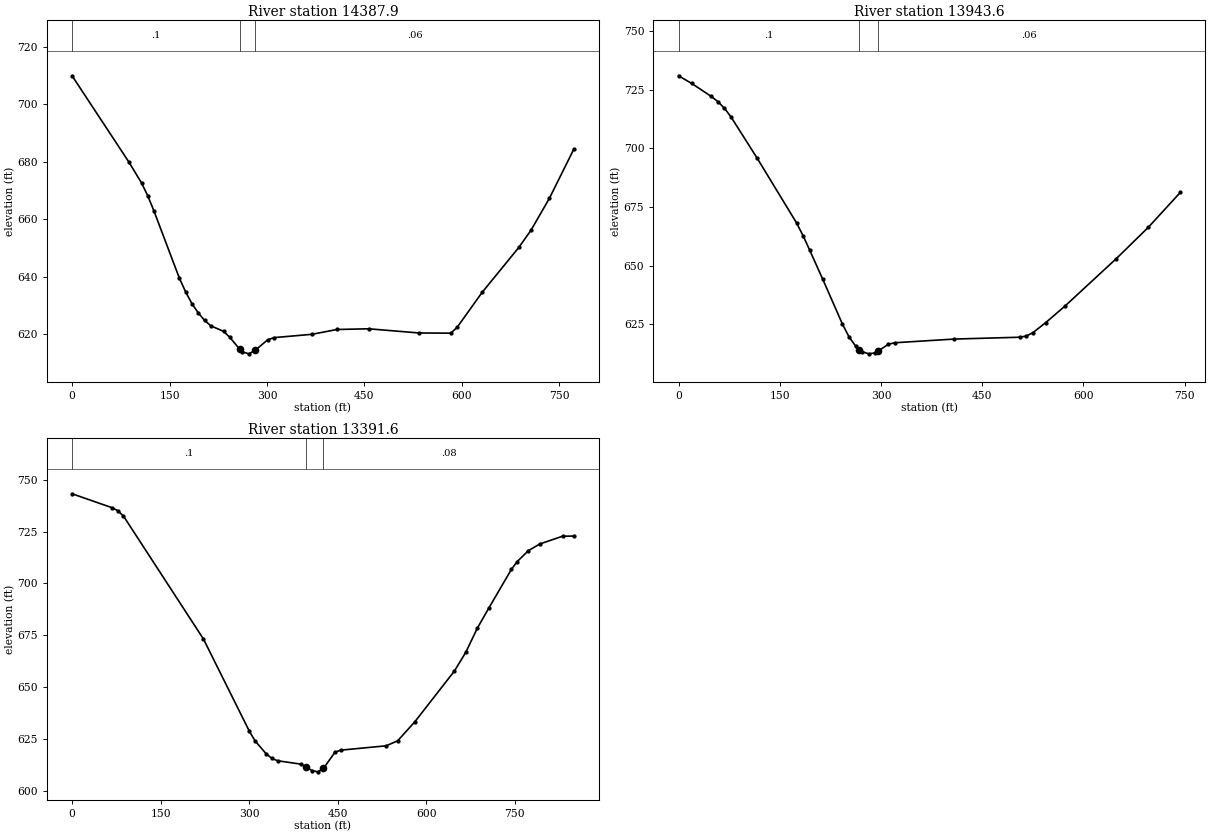
Type RM Length L Ch R = 1 ,14387.9 ,455.2,444.3,433.3
XS GIS Cut Line= 4
     1479301.129      319085.622     1479155.295      319254.893
     1478978.212      319611.664     1478931.337      319754.893
#Sta/Elev= 30
       0  709.92    87.4  679.94   106.9  672.68   116.6  668.15   126.3  662.76
   165.1  639.59   174.9  634.73   184.6  630.66   194.3  627.46     204  624.85
   213.7  622.96   233.1  621.08   242.9  618.96  258.42  614.75   262.3  613.94
     272  613.24   281.7  614.44   301.2  618.13   310.9  618.88   369.2  620.03
     408  621.71   456.6  621.95   534.3  620.49   582.9  620.43   592.6  622.42
   631.2  634.61   687.7  650.24   706.5  656.24   734.8  667.34   772.4  684.44
#Mann= 3 , 0 , 0
       0      .1       0  258.42    .045       0   281.7     .06       0
Bank Sta=258.42,281.7
XS Rating Curve= 0 ,0
Exp/Cntr=0.3,0.1

Type RM Length L Ch R = 1 ,13943.6 ,560.6,552,542.8
XS GIS Cut Line= 3
     1478704.775      318994.476     1478717.795      319538.747
     1478694.358      319736.664
#Sta/Elev= 30
       0  730.86    19.4  727.62    48.6  722.04    58.3  719.85      68  717.04
    77.8  713.32   116.7  695.68     175  668.13   184.7  662.65   194.4  656.57
   213.9  644.08     243  625.01   252.8  619.57   262.5  615.68  267.89  614.21
   272.2  613.31   281.9   612.4   291.7  612.83  296.02  613.61   311.1   616.5
   320.8  617.13   408.3  618.69   505.5  619.48   515.3  619.97     525  621.39
   544.4  625.74   572.9  632.79   648.8  652.96   696.3  666.31   743.7  681.17
#Mann= 3 , 0 , 0
       0      .1       0  267.89    .045       0  296.02     .06       0
Bank Sta=267.89,296.02
XS Rating Curve= 0 ,0
Exp/Cntr=0.3,0.1

Type RM Length L Ch R = 1 ,13391.6 ,418.8,405.9,392.7
XS GIS Cut Line= 3
       1478023.7      319008.554     1478241.233      319504.893
     1478361.025      319788.747
#Sta/Elev= 30
       0  743.19    67.7  736.49    77.4  735.05    87.1  732.45   222.6  673.21
     300  629.01   309.7  624.29     329  617.89   338.7  615.71   348.4   614.6
   387.1     613   396.8  611.54   406.4  609.89   416.1  609.27   425.8  610.89
   445.2  618.67   454.8  619.71   532.2  621.81   551.5  624.21   580.4   633.3
   647.8  657.88   667.1  666.93   686.3  678.36   705.6  687.98   744.1  706.73
   753.7  710.45     773   715.8   792.2     719   830.8  722.75     850  722.82
#Mann= 3 , 0 , 0
       0      .1       0   396.8    .045       0   425.8     .08       0
Bank Sta=396.8,425.8
XS Rating Curve= 0 ,0
Exp/Cntr=0.3,0.1