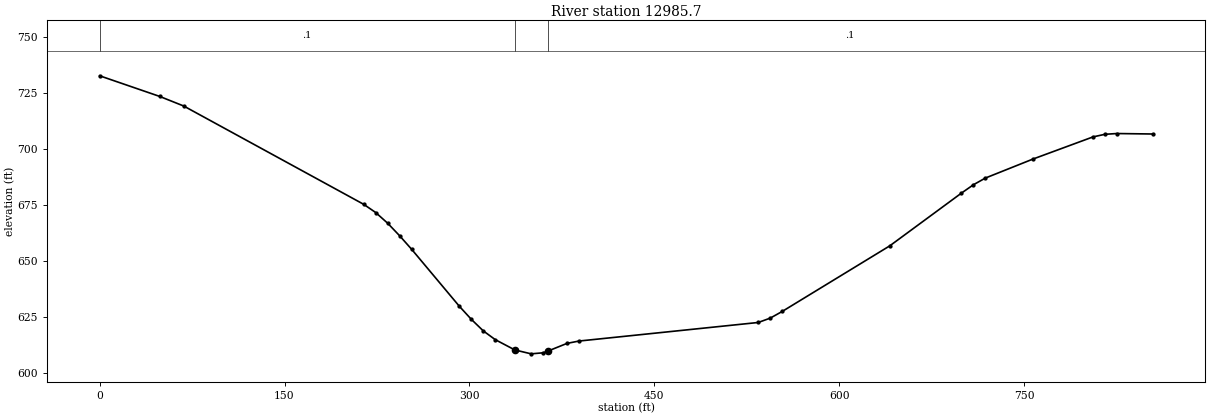
HEC-RAS study FrenchCr.prj: FrenchCr

--- FrenchCr.g01 (geometry) --- (continued)

Type RM Length L Ch R = 1 ,12985.7 ,12980.6,12985.7,12990.1
XS GIS Cut Line= 3
      1477533.62      319363.508     1477714.395      319478.628
     1478249.255      319830.375
#Sta/Elev= 30
       0  732.53    48.7  723.32    68.2  719.04   214.3  675.14     224  671.49
   233.7  666.72   243.4  661.12   253.1  655.12   291.9  629.62   301.6  623.81
   311.3  618.65     321  614.75   336.9  610.15   350.1  608.41   359.8  608.87
   363.4  609.57   379.2  613.07   388.9  614.12   534.4  622.41   544.1  624.35
   553.8  627.32   641.1  656.61   699.3  680.17     709  683.89   718.7  686.88
   757.5   695.4     806  705.24   815.7  706.41   825.4  706.75   854.5  706.54
#Mann= 3 , 0 , 0
       0      .1       0   336.9    .045       0   363.4      .1       0
Bank Sta=336.9,363.4
XS Rating Curve= 0 ,0
Exp/Cntr=0.3,0.1

Chan Stop Cuts=-1
Use User Specified Reach Order=0
Composite Channel Slope=5